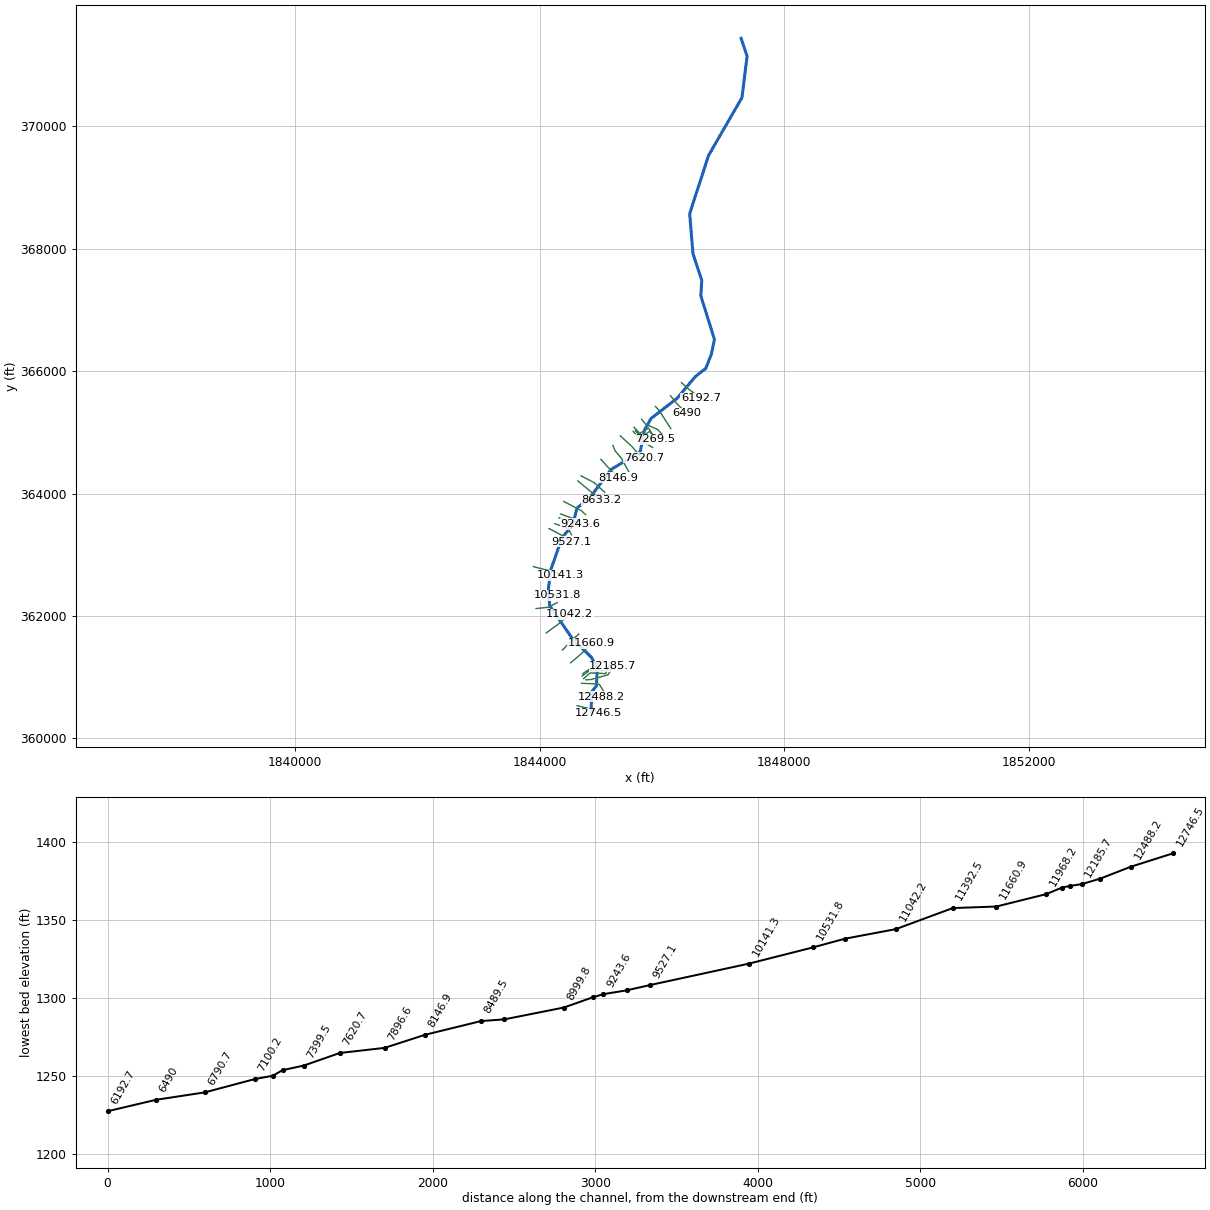
--- FIFTENMIFK.prj (project) ---

Proj Title=FIFTENMIFK
Current Plan=p01
Default Exp/Contr=0,0
English Units
Geom File=g01
Flow File=f01
Plan File=p01
BEGIN DESCRIPTION:
END DESCRIPTION:
DSS Export Rating Curves= 0
DSS Export Rating Curve Sorted= 0
DSS Export Volume Flow Curves= 0
DXF OffsetX= 0
DXF OffsetY= 0
DXF ScaleX= 0
DXF ScaleY= 0

--- FIFTENMIFK.p01 (plan) ---

Plan Title=Floodplain
Program Version=4.00
Geom File=g01
Flow File=f01
K Sum by GR=0
Std Step Tol=0.01
Critical Tol=0.01
Num of Std Step Trials=20
Max Error Tol=0.3
Flow Tol Ratio=0.001
Split Flow NTrial=30
Split Flow Tol=0.02
Split Flow Ratio=0.02
Log Output Level=0
Friction Slope Method=1
Unsteady Friction Slope Method=2
Unsteady Bridges Friction Slope Method=1
Global Log Level=0
CheckData=False
Run HTab=0
Run UNet=0
Run PostProcess=0
UNET Theta=0
UNET Theta Warmup=0
UNET ZTol=0
UNET ZSATol=0
UNET MxIter=0
UNET MaxInSteps=0
UNET DtIC=0
UNET DtMin=0
UNET MaxCRTS=0
UNET WFStab=0
UNET SFStab=0
UNET WFX=0
UNET SFX=0
UNET DSS MLevel=0
UNET DZMax Abort=0
UNET Convert EG Bridges=0
UNET Use Existing IB Tables=0
UNET Froude Limit=0
UNET Froude Power=0
Write IC File=0
Echo Input=False
Echo Output=False
Write Detailed=0

--- FIFTENMIFK.f01 (steady flow) ---

Flow Title=NFF Regression Equation
Program Version=4.10
Number of Profiles= 1
Profile Names=P100yr
River Rch & RM=FIFTENMIFK,Main            ,12746.5
879.2402
River Rch & RM=FIFTENMIFK,Main            ,12299.3
881.1222
River Rch & RM=FIFTENMIFK,Main            ,12063.9
1364.765
River Rch & RM=FIFTENMIFK,Main            ,10141.3
1420.955
River Rch & RM=FIFTENMIFK,Main            ,4829.2
1576.399
River Rch & RM=FIFTENMIFK,Main            ,4202.6
2018.235
River Rch & RM=FIFTENMIFK,Main            ,584.1
2138.645
Boundary for River Rch & Prof#=FIFTENMIFK,Main            , 1
Up Type= 0
Dn Type= 3
Dn Slope=0.012
DSS Import GetInterval= 0
DSS Import GetPeak= 0
DSS Import FillOption= 0

--- FIFTENMIFK.g01 (geometry) ---

Geom Title=USGS 10m DEM
Program Version=4.10

River Reach=FIFTENMIFK      ,Main
Reach XY= 30
     1844842.068       360434.33     1844848.969      360757.942
     1844927.745      360857.421     1844943.611      361150.161
     1844847.083      361322.817     1844527.031       361641.48
     1844163.923      362168.043     1844142.222      362440.178
     1844181.718      362752.765      1844364.27       363276.81
     1844542.996      363490.815     1844609.402      363762.191
     1844825.656      363940.142     1845165.717       364393.05
      1845643.35      364678.864     1845712.053      365035.057
     1845819.128      365224.906     1846247.503      365557.097
     1846548.481      365914.305       1846717.1      366045.273
     1846808.724      366279.865     1846858.018      366520.441
     1846636.143      367230.467     1846651.016      367485.538
     1846507.145      367923.653     1846453.101      368573.826
     1846762.689      369526.538      1847308.09      370470.282
     1847392.412      371147.591     1847294.214      371439.367

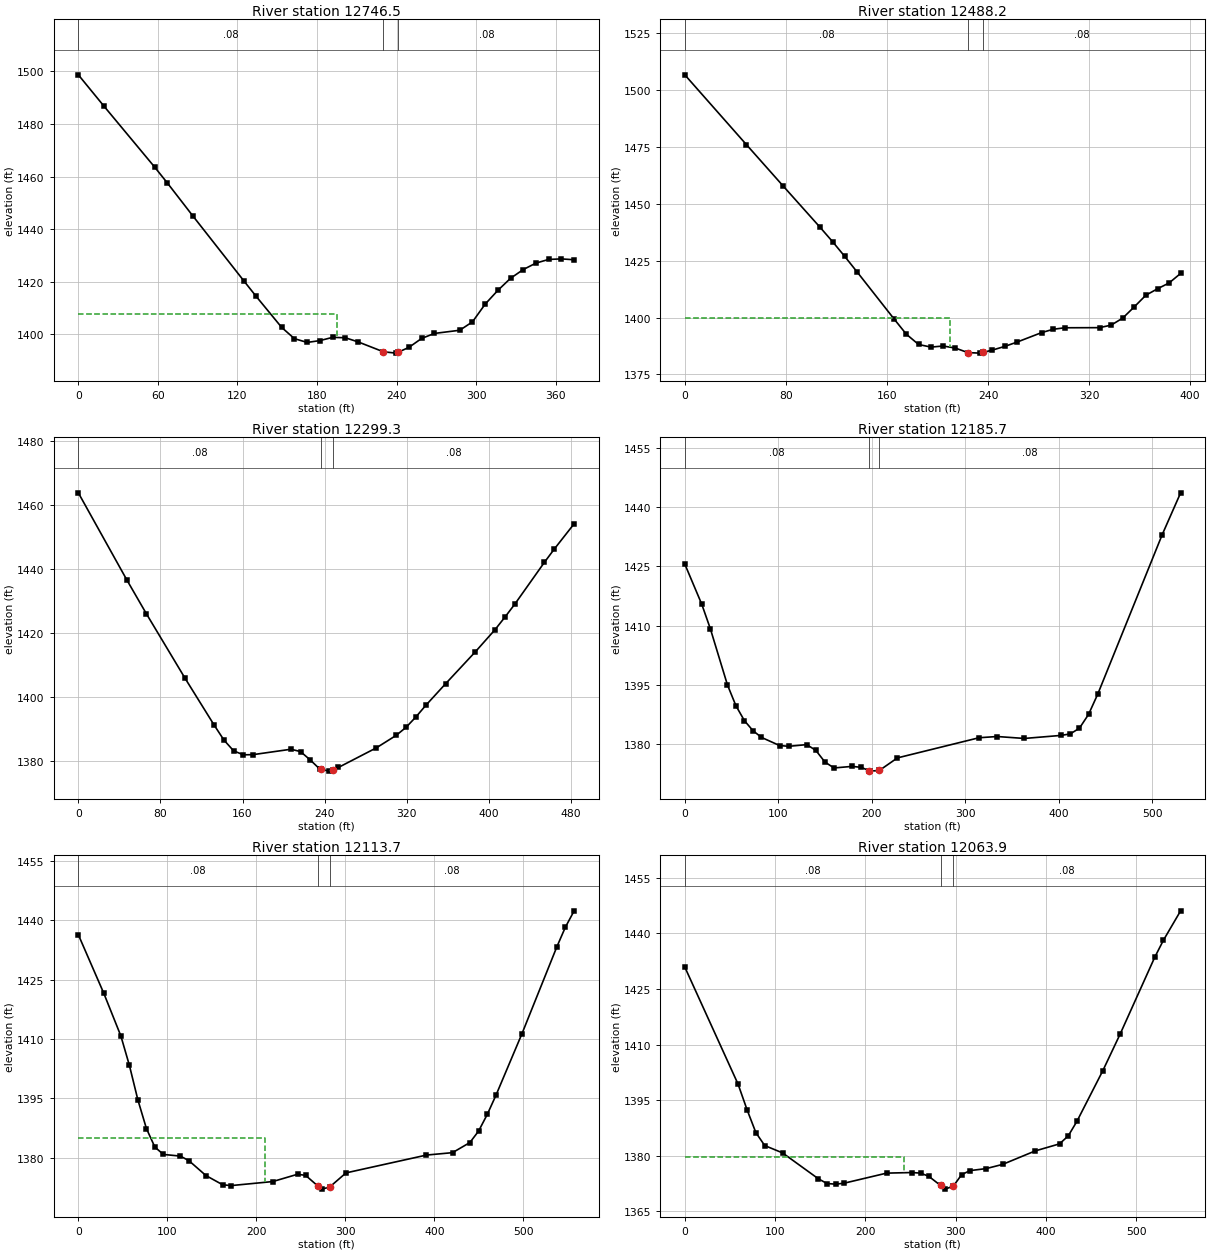
Type RM Length L Ch R = 1 ,12746.5 ,253.5,258.3,262.3
XS GIS Cut Line= 3
     1844613.109      360533.686     1844901.847       360463.02
      1844955.64      360408.229
#Sta/Elev= 30
       0 1498.72    19.2 1486.89    57.5 1463.68    67.1 1457.63    86.3 1445.12
   124.7 1420.47   134.2 1414.44   153.4 1402.67     163  1398.4   172.6 1396.97
   182.2 1397.66   191.8  1398.9   201.4 1398.74     211 1397.18   230.1 1393.41
   239.7  1392.9   241.51393.307   249.3 1395.07   258.9 1398.47   268.5 1400.38
   287.7  1401.6   297.3 1404.79   306.9 1411.55   316.5 1416.79     326 1421.35
   335.6 1424.68   345.2 1427.14   354.8 1428.53   364.4 1428.73     374  1428.4
#Mann= 3 , 0 , 0
       0     .08       0   230.1    .045       0   241.5     .08       0
#XS Ineff= 2 , 0
          194.86  1407.7
Permanent Ineff=
       F       F
Bank Sta=230.1,241.5
XS Rating Curve= 0 ,0
Exp/Cntr=0.3,0.1

Type RM Length L Ch R = 1 ,12488.2 ,188.9,188.9,186.8
XS GIS Cut Line= 3
     1844623.924      360742.292     1844906.028      360729.211
     1845006.141      360683.577
#Sta/Elev= 30
       0 1506.63    48.7    1476    77.9 1457.75   107.1 1439.62   116.9 1433.37
   126.6 1426.84   136.3 1420.08   165.6 1399.39   175.3  1392.7     185 1388.17
   194.8 1387.02   204.5  1387.5   214.2 1386.58     224  1384.6   233.7 1384.37
   235.9 1384.67   243.4  1385.7   253.2 1387.32   262.9 1389.21   282.4 1393.39
   291.6 1394.85   300.7 1395.51   328.2 1395.56   337.4 1396.67   346.6 1399.77
   355.8 1404.74   364.9 1409.81   374.1 1412.63   383.3 1415.21   392.4 1419.38
#Mann= 3 , 0 , 0
       0     .08       0     224    .045       0   235.9     .08       0
#XS Ineff= 2 , 0
       0     210    1400               0
Permanent Ineff=
       F       F
Bank Sta=224,235.9
XS Rating Curve= 0 ,0
Exp/Cntr=0.3,0.1

Type RM Length L Ch R = 1 ,12299.3 ,104.4,113.6,120.4
XS GIS Cut Line= 4
     1844684.929       360899.26     1844855.068      360893.184
     1844974.859      360883.635      1845077.29      360720.441
#Sta/Elev= 30
       0  1463.8    47.3 1436.52    66.2 1426.01     104 1405.76   132.4 1391.08
   141.9 1386.42   151.3 1383.06   160.8 1381.81   170.2 1381.87   207.2 1383.56
   216.5 1382.82   225.7 1380.28     235 1377.44   236.3 1377.34   244.2 1376.71
     2481377.186   253.4 1377.86   290.4    1384   309.7  1387.9   319.3 1390.41
     329  1393.7   338.6 1397.31   357.9 1404.08   386.8 1414.04     406 1420.98
   415.7 1424.92   425.3 1428.98   454.2 1442.09   463.8 1446.23   483.1 1454.12
#Mann= 3 , 0 , 0
       0     .08       0   236.3    .045       0     248     .08       0
Bank Sta=236.3,248
XS Rating Curve= 0 ,0
Exp/Cntr=0.3,0.1

Type RM Length L Ch R = 1 ,12185.7 ,78.9,72,63.9
XS GIS Cut Line= 4
     1844755.693       360957.02     1844837.637      360961.187
     1845118.193       361038.27     1845197.359      361174.382
#Sta/Elev= 30
       0  1425.6    18.2  1415.4    27.4 1409.18    45.6 1395.03    54.7 1389.74
    63.8 1385.96    72.9 1383.44      82 1381.73   101.4 1379.67   111.2 1379.47
   130.5  1379.9   140.2 1378.44   149.9  1375.5   159.6 1373.99     179 1374.39
   188.7 1374.15     197 1373.33   198.4 1373.19   208.1 1373.35   227.5 1376.54
   314.8 1381.64   334.2 1381.95   363.3 1381.46   402.5 1382.23   412.4 1382.61
   422.2 1384.05     432 1387.55   441.9 1392.72   510.8 1433.05   530.5 1443.63
#Mann= 3 , 0 , 0
       0     .08       0     197    .045       0   208.1     .08       0
Bank Sta=197,208.1
XS Rating Curve= 0 ,0
Exp/Cntr=0.3,0.1

Type RM Length L Ch R = 1 ,12113.7 ,49.3,49.8,49.1
XS GIS Cut Line= 6
     1844718.522      360976.777     1844827.984      361069.399
     1844921.734      361065.059     1845021.561      361061.586
      1845075.38      361056.378     1845159.147      361199.694
#Sta/Elev= 30
       0 1436.32    28.7 1421.48    47.8 1410.75    57.4 1403.31    66.9 1394.62
    76.5 1387.38      86 1382.69    95.6 1380.83   114.7 1380.41   124.3 1379.25
   143.4  1375.5   162.2 1373.17   171.5 1372.96   218.5 1373.98   246.3 1375.82
   255.4 1375.55     2691372.886   273.6 1372.07   282.4 1372.59   300.8 1376.17
   391.2 1380.67   420.5 1381.28     440 1383.83   449.8 1386.73   459.6 1390.96
   469.3 1395.76   498.6 1411.35   537.7 1433.23   547.4 1438.25   557.2 1442.35
#Mann= 3 , 0 , 0
       0     .08       0     269    .045       0   282.4     .08       0
#XS Ineff= 2 , 0
       0     210    1385               0
Permanent Ineff=
       F       F
Bank Sta=269,282.4
XS Rating Curve= 0 ,0
Exp/Cntr=0.3,0.1

Type RM Length L Ch R = 1 ,12063.9 ,81.8,95.7,108.4
XS GIS Cut Line= 6
     1844695.276       361019.52     1844830.415       361118.01
     1844924.165       361113.67     1845023.991      361110.197
     1845077.811      361104.989     1845150.831      361217.437
#Sta/Elev= 30
       0 1430.93      59 1399.32    68.9 1392.44    78.7 1386.24    88.5 1382.74
   108.2 1380.77   147.6 1373.83   157.4 1372.49   167.2 1372.32   176.6 1372.59
   223.5  1375.3   251.7 1375.46   261.1  1375.3   270.2 1374.44   283.3 1371.96
   288.3 1370.98   297.4 1371.79   306.5 1374.86   315.6 1375.97   333.7 1376.52
   351.9 1377.65     388 1381.29     415  1383.2   424.6 1385.34   434.2 1389.26
   462.9 1402.94   482.1 1412.83   520.4 1433.56     530 1438.15   549.1 1446.11
#Mann= 3 , 0 , 0
       0     .08       0   283.3    .045       0   297.4     .08       0
#XS Ineff= 2 , 0
          242.92 1379.54
Permanent Ineff=
       F       F
Bank Sta=283.3,297.4
XS Rating Curve= 0 ,0
Exp/Cntr=0.3,0.1

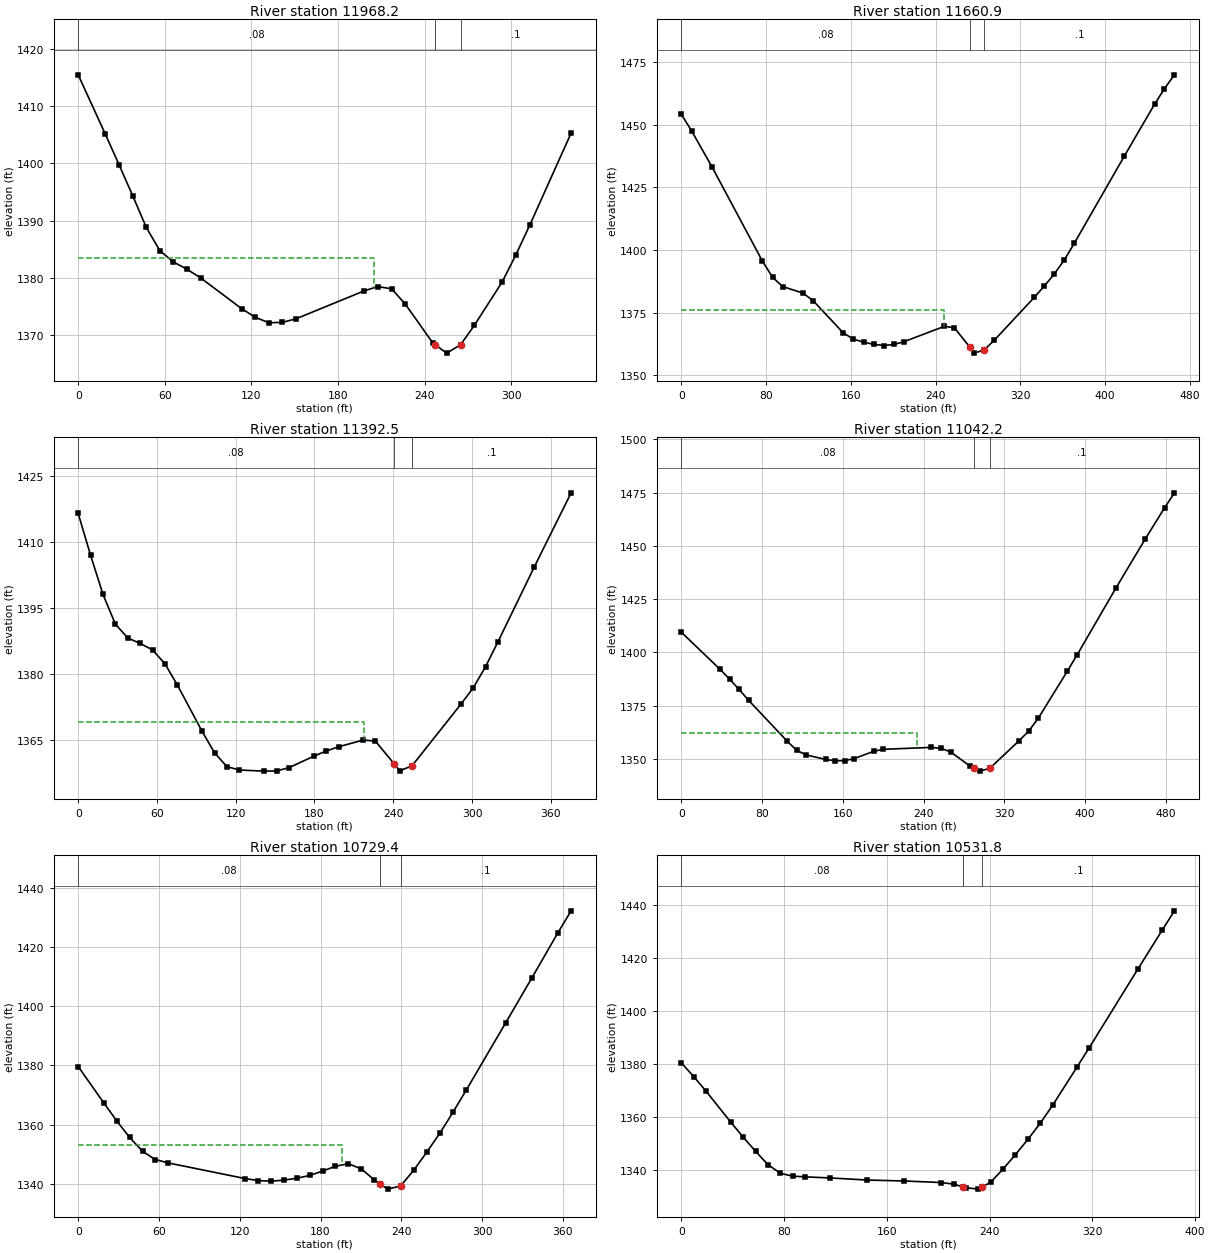
Type RM Length L Ch R = 1 ,11968.2 ,299.1,307.3,311.4
XS GIS Cut Line= 3
     1844704.877      361055.759     1844874.942      361174.619
     1844989.599      361243.953
#Sta/Elev= 27
       0 1415.47    18.9 1405.05    28.3 1399.76    37.7 1394.37    47.2 1388.79
    56.6 1384.71      66 1382.76    75.4 1381.48    84.9 1379.96   113.2  1374.6
   122.6  1373.1     132 1372.13   141.5  1372.2   150.9 1372.82     198 1377.69
   207.5 1378.45   217.1 1378.07   226.6  1375.4   245.8 1368.55   247.1 1368.31
   255.3 1366.82   264.9 1368.28   274.5  1371.7   293.6 1379.21   303.2 1383.99
   312.8 1389.17   341.5  1405.3
#Mann= 3 , 0 , 0
       0     .08       0   247.1    .045       0   264.9      .1       0
#XS Ineff= 2 , 0
          204.92 1383.42
Permanent Ineff=
       F       F
Bank Sta=247.1,264.9
XS Rating Curve= 0 ,0
Exp/Cntr=0.3,0.1

Type RM Length L Ch R = 1 ,11660.9 ,268,268.4,264.6
XS GIS Cut Line= 3
     1844508.696      361234.969     1844689.729      361390.732
     1844844.634      361556.149
#Sta/Elev= 30
       0 1454.11     9.6 1447.52    28.7 1433.28    76.4 1395.58      86 1389.13
    95.5 1385.44   114.6 1382.81   124.2 1379.82   152.8 1366.91   162.4 1364.42
     172 1363.22   181.5 1362.37   191.1 1361.89   200.6  1362.3   210.2 1363.43
   248.3 1369.56   257.7 1368.95     2721361.364   276.6 1358.85     286 1360.22
   295.5 1364.07   333.2 1381.16   342.7 1385.69   352.1 1390.52   361.6 1396.13
     371  1402.8   418.2 1437.57   446.6 1458.17     456 1464.43   465.4 1469.94
#Mann= 3 , 0 , 0
       0     .08       0     272    .045       0     286      .1       0
#XS Ineff= 2 , 0
          247.56 1376.25
Permanent Ineff=
       F       F
Bank Sta=272,286
XS Rating Curve= 0 ,0
Exp/Cntr=0.3,0.1

Type RM Length L Ch R = 1 ,11392.5 ,350.3,350.3,348.8
XS GIS Cut Line= 3
     1844371.977      361443.302     1844517.377       361591.74
      1844640.64      361705.455
#Sta/Elev= 30
       0 1416.55     9.4 1407.08    18.9 1398.11    28.3 1391.36    37.8 1388.18
    47.2 1386.95    56.7 1385.46    66.1 1382.29    75.6 1377.45    94.4  1366.9
   103.9 1362.01   113.3 1358.87   122.8  1358.1   141.7 1357.85   151.1  1357.9
   160.6 1358.64   179.4 1361.24   188.9 1362.44   198.3 1363.39   217.1 1364.93
   226.4 1364.69   240.9 1359.43     245  1357.9   254.4  1359.1   291.6 1373.13
     301 1376.86   310.3 1381.64   319.6 1387.22   347.5 1404.41   375.5 1421.26
#Mann= 3 , 0 , 0
       0     .08       0   240.9    .045       0   254.4      .1       0
#XS Ineff= 2 , 0
       0     218 1369.08               0
Permanent Ineff=
       F       F
Bank Sta=240.9,254.4
XS Rating Curve= 0 ,0
Exp/Cntr=0.3,0.1

Type RM Length L Ch R = 1 ,11042.2 ,317.4,312.8,307
XS GIS Cut Line= 3
     1844107.944      361723.105     1844300.304      361863.285
     1844490.756      362026.057
#Sta/Elev= 30
       0 1409.44    38.1 1392.17    47.6 1387.54    57.1 1382.67    66.6 1377.53
   104.7 1358.45   114.2 1354.07   123.8 1351.92   142.8 1349.85   152.3 1349.19
   161.8 1349.26   171.4 1350.25   190.4 1353.63   199.9 1354.58   247.6 1355.49
   257.3 1355.06   266.9 1353.31   286.2 1346.65     2901345.741   295.8 1344.35
   305.5 1345.65   334.4 1358.49     344 1363.06   353.6 1369.11   382.6 1391.36
   392.2 1398.93   430.7 1430.32   459.6 1453.19   478.9 1467.92   488.6  1474.9
#Mann= 3 , 0 , 0
       0     .08       0     290    .045       0   305.5      .1       0
#XS Ineff= 2 , 0
          232.95 1362.32
Permanent Ineff=
       F       F
Bank Sta=290,305.5
XS Rating Curve= 0 ,0
Exp/Cntr=0.3,0.1

Type RM Length L Ch R = 1 ,10729.4 ,208.2,197.6,186.5
XS GIS Cut Line= 3
     1843942.187      362121.149     1844141.615      362142.531
     1844288.552      362218.663
#Sta/Elev= 30
       0 1379.61    19.1 1367.28    28.6 1361.29    38.2 1355.68    47.8 1350.98
    57.3 1348.21    66.9 1347.06   124.2 1341.77   133.7  1341.1   143.3 1340.91
   152.8 1341.26   162.4  1341.9   171.9 1342.83   181.5 1344.31     191 1345.94
   200.6  1346.8   210.3 1345.05     220  1341.3   224.4 1339.92   229.8 1338.22
   239.4 1339.26   249.2  1344.6     259 1350.78   268.7 1357.17   278.4 1364.22
   288.2 1371.65   317.4  1394.3   336.9 1409.51   356.3  1424.8   366.1 1432.19
#Mann= 3 , 0 , 0
       0     .08       0   224.4    .045       0   239.4      .1       0
#XS Ineff= 2 , 0
          196.28 1353.06
Permanent Ineff=
       F       F
Bank Sta=224.4,239.4
XS Rating Curve= 0 ,0
Exp/Cntr=0.3,0.1

Type RM Length L Ch R = 1 ,10531.8 ,395,390.5,383.6
XS GIS Cut Line= 3
     1843916.103      362350.277     1844214.715      362350.116
     1844298.916      362336.821
#Sta/Elev= 30
       0 1380.28     9.6 1375.15    19.3 1369.56    38.5 1357.87    48.2  1352.2
    57.8 1346.86    67.4 1341.85    77.1 1338.58    86.7 1337.53    96.3 1337.26
   115.6 1336.85   144.5 1336.06   173.4  1335.7   202.3 1335.11   211.9 1334.51
   219.3 1333.49   221.6 1333.17   231.2 1332.62   234.3 1333.46   240.8 1335.22
   250.4 1340.21   260.1 1345.67   269.7  1351.4   279.4 1357.53     289  1364.3
   308.1 1378.83   317.6 1386.14   355.4  1415.8   374.4 1430.56   383.9 1437.86
#Mann= 3 , 0 , 0
       0     .08       0   219.3    .045       0   234.3      .1       0
Bank Sta=219.3,234.3
XS Rating Curve= 0 ,0
Exp/Cntr=0.3,0.1

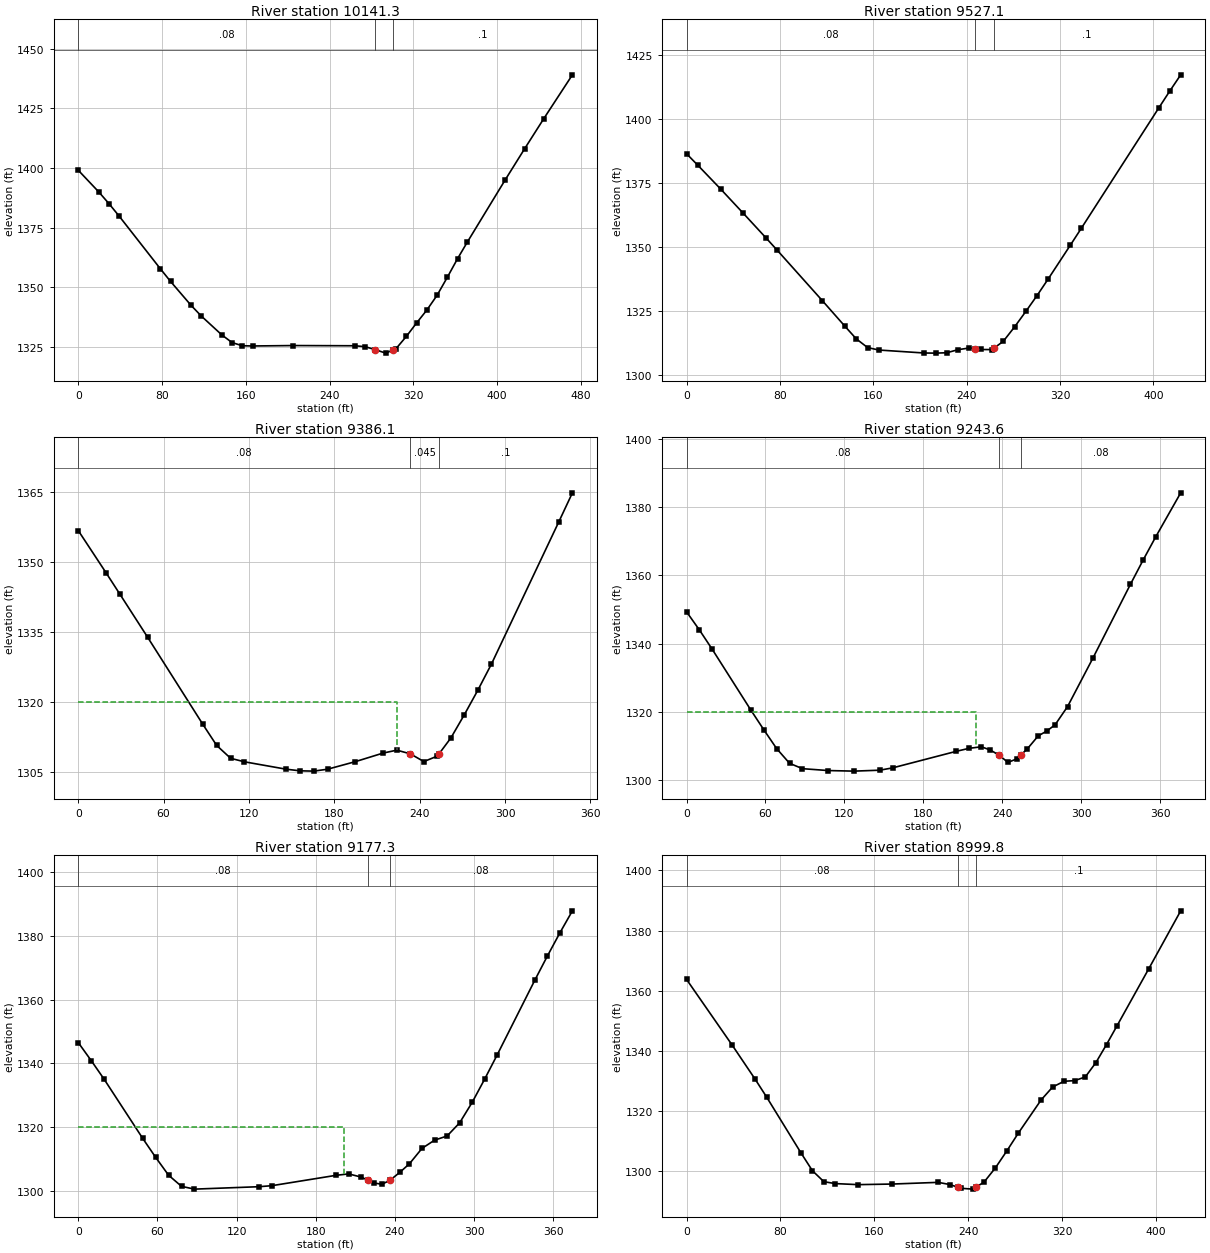
Type RM Length L Ch R = 1 ,10141.3 ,618.3,614.2,608
XS GIS Cut Line= 3
     1843896.773      362806.475     1844247.778      362717.335
     1844343.187       362663.21
#Sta/Elev= 30
       0 1399.05    19.6 1389.94    29.4 1384.99    39.2 1379.71    78.3 1357.75
    88.1  1352.4   107.7 1342.36   117.4  1337.9     137 1329.98   146.8 1326.74
   156.6  1325.4   166.4  1325.3   205.5 1325.48   264.3 1325.39   274.1 1324.99
   283.8 1323.72   293.6  1322.3   300.5 1323.62   303.4 1324.18   313.2 1329.28
     323 1334.94   332.8 1340.36   342.6 1346.57   352.4 1354.14   362.2 1361.98
   371.3 1368.77   407.8 1395.12   426.1 1408.01   444.4 1420.65   471.8 1439.09
#Mann= 3 , 0 , 0
       0     .08       0   283.8    .045       0   300.5      .1       0
Bank Sta=283.8,300.5
XS Rating Curve= 0 ,0
Exp/Cntr=0.3,0.1

Type RM Length L Ch R = 1 ,9527.1  ,152.3,141.1,127.9
XS GIS Cut Line= 3
     1844152.322      363428.988     1844409.786      363293.757
     1844514.541      363212.515
#Sta/Elev= 30
       0 1386.44     9.7 1381.92    29.1 1372.69    48.5  1363.2    67.9  1353.6
    77.6 1348.73   116.3 1328.98   135.7 1318.94   145.4 1314.02   155.1 1310.61
   164.8 1309.64   203.6 1308.48   213.3 1308.43     223 1308.58   232.6 1309.78
   242.4 1310.45     2471310.165     252 1309.85   261.7 1309.81     2631310.245
   271.4 1313.06   281.1 1318.72   290.8 1324.81   300.3 1330.95   309.8 1337.41
   328.7 1350.57   338.2 1357.25   404.4 1404.22   413.9 1410.88   423.4 1417.32
#Mann= 3 , 0 , 0
       0     .08       0     247    .045       0     263      .1       0
Bank Sta=247,263
XS Rating Curve= 0 ,0
Exp/Cntr=0.3,0.1

Type RM Length L Ch R = 1 ,9386.1  ,123.8,142.5,170.3
XS GIS Cut Line= 3
     1844249.546      363507.931     1844460.483      363432.931
     1844522.462      363326.161
#Sta/Elev= 25
       0 1356.72    19.5 1347.68    29.2  1343.1    48.7 1333.86    87.6 1315.13
    97.3 1310.62   107.1 1307.86   116.8 1307.11     146 1305.53   155.7 1305.18
   165.5 1305.11   175.2 1305.52   194.7 1307.14   214.1 1308.97   223.9 1309.61
   233.4 1308.82   242.9 1307.16   252.4 1308.34   253.41308.749   261.9 1312.23
   271.4 1317.24   280.8 1322.45   290.4 1328.08   337.8 1358.62   347.3 1364.81
#Mann= 3 , 0 , 0
       0     .08       0   233.4    .045       0   253.4      .1       0
#XS Ineff= 2 , 0
       0  223.83    1320               0
Permanent Ineff=
       F       F
Bank Sta=233.4,253.4
XS Rating Curve= 0 ,0
Exp/Cntr=0.3,0.1

Type RM Length L Ch R = 1 ,9243.6  ,68.1,66.2,64.7
XS GIS Cut Line= 6
     1844315.116       363605.31     1844489.595      363541.074
     1844526.054       363529.79     1844552.529        363526.1
      1844580.09      363535.432     1844670.238      363503.791
#Sta/Elev= 30
       0 1349.34     9.8 1344.01    19.6 1338.31    48.9 1320.54    58.7  1314.8
    68.5 1309.26    78.3 1304.96    88.1 1303.39   107.6 1302.84   127.2 1302.67
   146.8 1302.94   156.6 1303.62     205 1308.47   214.6 1309.34   224.1  1309.8
   230.9 1308.85   237.6 1307.33   244.3 1305.22   250.9 1306.25     2541307.375
   259.1 1309.23   267.3    1313   273.7 1314.39   280.1 1316.23   289.6 1321.58
   308.8 1335.73   337.4 1357.41     347 1364.48   356.5 1371.23   375.6  1384.2
#Mann= 3 , 0 , 0
       0     .08       0   237.6    .045       0     254     .08       0
#XS Ineff= 2 , 0
       0  220.02    1320               0
Permanent Ineff=
       F       F
Bank Sta=237.6,254
XS Rating Curve= 0 ,0
Exp/Cntr=0.3,0.1

Type RM Length L Ch R = 1 ,9177.3  ,181.4,177.5,162.5
XS GIS Cut Line= 6
     1844341.809      363667.159     1844516.288      363602.923
     1844552.746      363591.638     1844564.899      363589.902
     1844578.571      363595.328     1844687.946      363537.819
#Sta/Elev= 30
       0 1346.54     9.8 1340.91    19.6 1335.07    48.9  1316.5    58.7 1310.57
    68.5 1304.97    78.3 1301.49    88.1 1300.62     137 1301.38   146.8  1301.7
   195.5 1304.95     205 1305.39   214.6 1304.38   219.71303.391   224.1 1302.54
   230.2 1302.15   236.2 1303.36   243.7 1305.85   251.1 1308.58   260.6 1313.39
   270.1 1315.96   279.6 1317.27   289.1 1321.38   298.6 1327.79   308.1  1335.1
   317.6  1342.7   346.1 1366.08   355.6 1373.63   365.1 1380.91   374.6 1387.82
#Mann= 3 , 0 , 0
       0     .08       0   219.7    .045       0   236.2     .08       0
#XS Ineff= 2 , 0
       0  201.59    1320               0
Permanent Ineff=
       F       F
Bank Sta=219.7,236.2
XS Rating Curve= 0 ,0
Exp/Cntr=0.3,0.1

Type RM Length L Ch R = 1 ,8999.8  ,368.6,366.6,360.1
XS GIS Cut Line= 3
     1844393.863      363871.401     1844678.857      363722.307
     1844752.319      363655.452
#Sta/Elev= 30
       0 1363.79      39 1341.88    58.5 1330.59    68.2  1324.7    97.5 1306.12
   107.2 1300.22     117 1296.56   126.7 1295.93   146.2 1295.58   175.4 1295.78
   214.4 1296.34   224.2 1295.62     2311294.744   233.9 1294.37   243.7 1294.09
     2471294.875   253.4  1296.4   263.2  1301.2   272.9 1306.81   282.6 1312.67
   302.1 1323.75   311.9 1328.04   321.6 1329.93   330.7 1330.16   339.7 1331.37
   348.7 1336.11   357.8 1342.16   366.8 1348.42   393.9 1367.42     421 1386.59
#Mann= 3 , 0 , 0
       0     .08       0     231    .045       0     247      .1       0
Bank Sta=231,247
XS Rating Curve= 0 ,0
Exp/Cntr=0.3,0.1

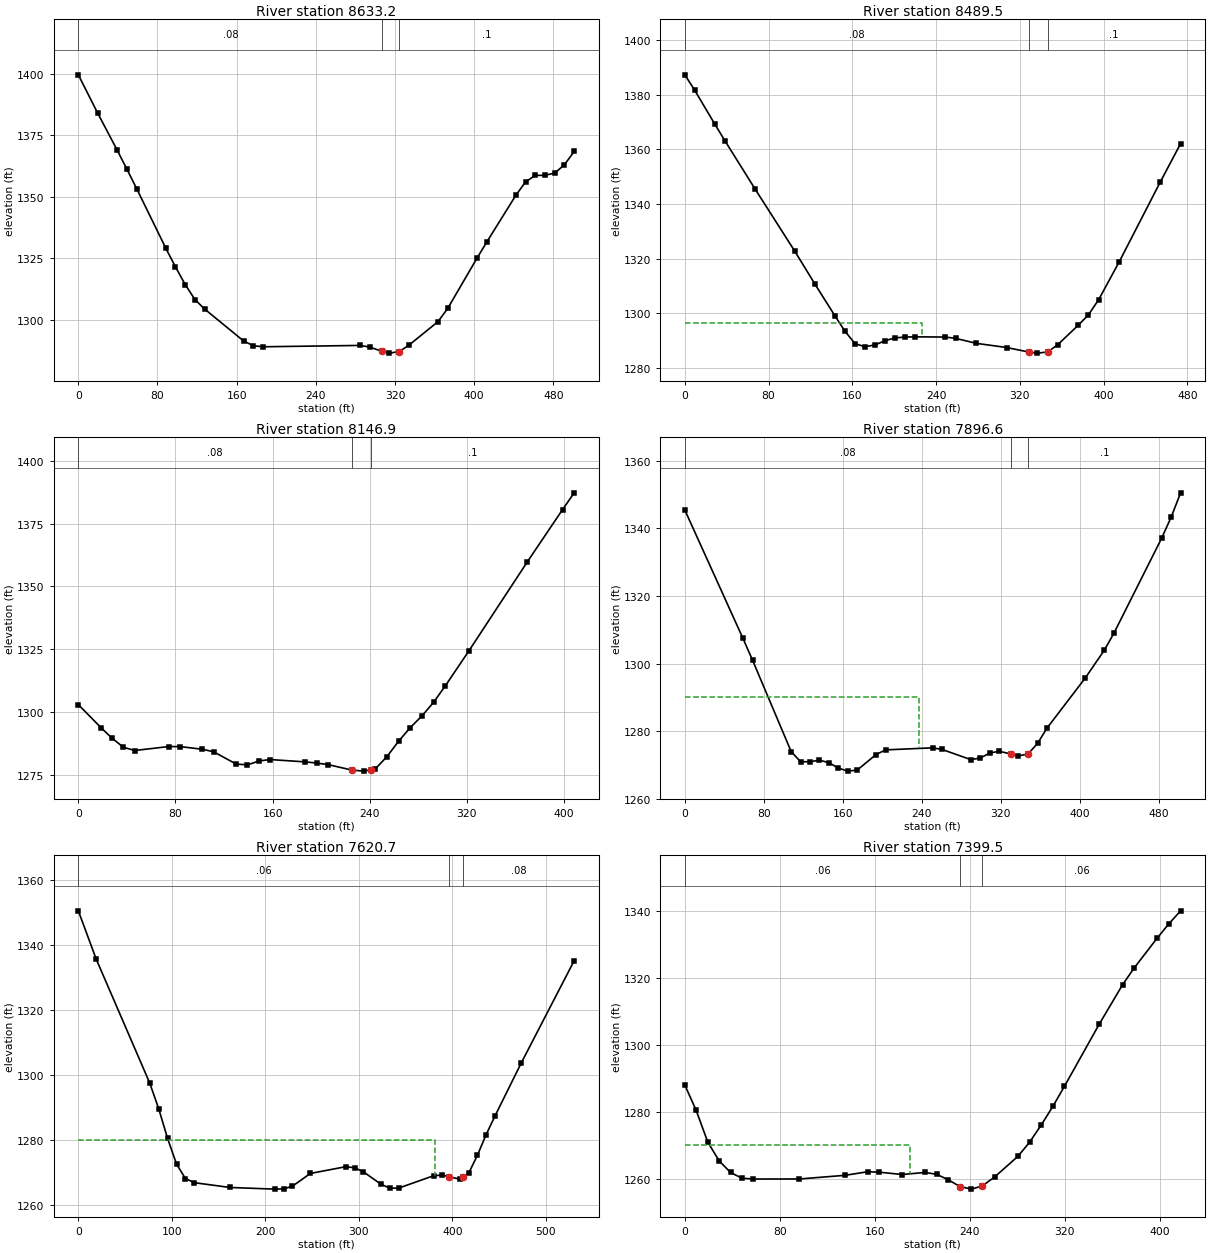
Type RM Length L Ch R = 1 ,8633.2  ,144.4,143.7,142.2
XS GIS Cut Line= 2
     1844623.696       364207.74     1845010.265      363888.927
#Sta/Elev= 30
       0 1399.55    19.6 1383.96    39.3 1368.92    49.1  1361.2      59 1353.28
    88.4 1329.12    98.2  1321.5   108.1 1314.29   117.9 1308.23   127.7 1304.39
     167 1291.44   176.8 1289.52   186.7 1289.08   284.9 1289.63   294.8 1288.93
   307.21287.169   314.4  1286.5   324.2 1287.12     334 1289.69   363.5  1299.3
   373.4 1304.72   402.8    1325   412.6 1331.51   442.1 1350.56     452 1356.08
   461.8 1358.68   471.6 1358.74   481.4 1359.63   491.2 1362.99   501.1 1368.42
#Mann= 3 , 0 , 0
       0     .08       0   307.2    .045       0   324.2      .1       0
Bank Sta=307.2,324.2
XS Rating Curve= 0 ,0
Exp/Cntr=0.3,0.1

Type RM Length L Ch R = 1 ,8489.5  ,342.8,342.6,339.4
XS GIS Cut Line= 3
     1844678.365      364289.512     1844890.518      364179.269
     1845063.781      364021.283
#Sta/Elev= 30
       0 1387.21     9.6 1381.49    28.7 1369.14    38.2 1363.17    66.9 1345.57
   105.2  1322.6   124.3 1310.64   143.4 1299.04     153 1293.39   162.6 1288.85
   172.1 1287.72   181.7  1288.4   191.3 1289.94   200.8 1290.96   210.4 1291.28
     220 1291.35   248.9 1291.27   258.6 1290.81   278.2 1288.98   307.5 1287.44
     3291285.754   336.8 1285.39   346.6 1285.81   356.3 1288.49   375.9 1295.64
   385.6 1299.43   395.4 1305.01     415 1318.84     454 1347.88   473.6 1362.06
#Mann= 3 , 0 , 0
       0     .08       0     329    .045       0   346.6      .1       0
#XS Ineff= 2 , 0
          226.75 1296.53
Permanent Ineff=
       F       F
Bank Sta=329,346.6
XS Rating Curve= 0 ,0
Exp/Cntr=0.3,0.1

Type RM Length L Ch R = 1 ,8146.9  ,255.5,250.3,243.5
XS GIS Cut Line= 3
     1845002.055      364559.774     1845107.557      364442.368
     1845281.045       364261.56
#Sta/Elev= 30
       0 1303.09    18.6 1293.94    27.8 1289.72    37.1 1286.13    46.4 1284.84
    74.3  1286.4    83.6  1286.4   102.1 1285.34   111.4 1284.34     130 1279.47
   139.3 1279.12   148.6 1280.66   157.8 1281.26   186.8 1280.32   196.4 1279.86
     206  1279.2   225.3 1277.07     235 1276.65   241.3 1277.23   244.6 1277.53
   254.2 1282.42   263.9  1288.6   273.5 1293.98   283.1 1298.62   292.8  1304.1
   302.4 1310.62   321.7 1324.42   369.9 1359.84   398.8 1380.51   408.4  1387.2
#Mann= 3 , 0 , 0
       0     .08       0   225.3    .045       0   241.3      .1       0
Bank Sta=225.3,241.3
XS Rating Curve= 0 ,0
Exp/Cntr=0.3,0.1

Type RM Length L Ch R = 1 ,7896.6  ,272,275.9,279.2
XS GIS Cut Line= 4
     1845197.712      364785.866     1845235.688        364695.4
     1845335.595      364579.764     1845456.392      364359.651
#Sta/Elev= 30
       0 1345.46    58.9 1307.46    68.7 1300.95   107.7    1274   117.2 1271.01
   126.8 1270.99   136.3 1271.48   145.9  1270.7   155.4 1269.14     165 1268.22
   174.5 1268.52   193.6 1273.11   203.2  1274.5   250.9 1275.11   260.6 1274.62
   289.6 1271.62   299.2  1272.1   308.9 1273.59   318.5 1274.08     3301273.303
   337.8 1272.75   347.5 1273.26   357.2 1276.45   366.8 1280.98   405.4 1295.74
   424.8 1304.01   434.4 1308.97   482.7 1337.05   492.4 1343.33     502 1350.52
#Mann= 3 , 0 , 0
       0     .08       0     330    .045       0   347.5      .1       0
#XS Ineff= 2 , 0
       0  237.56    1290               0
Permanent Ineff=
       F       F
Bank Sta=330,347.5
XS Rating Curve= 0 ,0
Exp/Cntr=0.3,0.1

Type RM Length L Ch R = 1 ,7620.7  ,211.6,221.2,228.7
XS GIS Cut Line= 5
     1845319.239      364943.852      1845515.42      364762.428
     1845588.251      364676.234     1845634.208      364617.357
      1845702.92      364586.213
#Sta/Elev= 30
       0 1350.52    19.1 1335.68    76.4 1297.52    85.9 1289.69    95.4 1280.57
     105 1272.63   114.5 1268.19   124.1 1266.91   162.2 1265.44     210 1264.93
   219.5    1265     229 1265.84   248.1 1269.75     286 1271.83   295.4 1271.49
   304.8 1270.26   323.6 1266.44     333 1265.24   342.4 1265.23     380 1269.06
   389.4 1269.26   396.71268.703   408.1    1268   411.71268.712   417.4 1269.84
   426.7  1275.3   436.1 1281.72   445.4 1287.34   473.6 1303.72   530.2 1335.17
#Mann= 3 , 0 , 0
       0     .06       0   396.7    .045       0   411.7     .08       0
#XS Ineff= 2 , 0
       0  381.05    1280               0
Permanent Ineff=
       F       F
Bank Sta=396.7,411.7
XS Rating Curve= 0 ,0
Exp/Cntr=0.3,0.1

Type RM Length L Ch R = 1 ,7399.5  ,103.2,130.1,153.5
XS GIS Cut Line= 3
     1845529.307      365015.423      1845662.64      364863.339
     1845847.362      364752.923
#Sta/Elev= 30
       0 1288.01     9.6 1280.41    19.3 1270.97    28.9 1265.35    38.5 1261.86
    48.2 1260.15    57.8 1259.91    96.3 1259.92   134.8 1261.01   154.1 1262.09
   163.7 1261.95     183 1261.26   202.3 1261.87     212 1261.32   221.8  1259.7
   231.6 1257.67   241.4 1256.89   250.5 1257.84     261 1260.55   280.5 1266.69
   290.3 1270.89   300.1 1276.04   309.9  1281.6   319.6 1287.56     349  1306.2
   368.6 1317.95   378.3 1322.94   397.9 1331.95   407.7 1336.21   417.5 1340.04
#Mann= 3 , 0 , 0
       0     .06       0   231.6    .045       0   250.5     .06       0
#XS Ineff= 2 , 0
       0     190    1270               0
Permanent Ineff=
       F       F
Bank Sta=231.6,250.5
XS Rating Curve= 0 ,0
Exp/Cntr=0.3,0.1

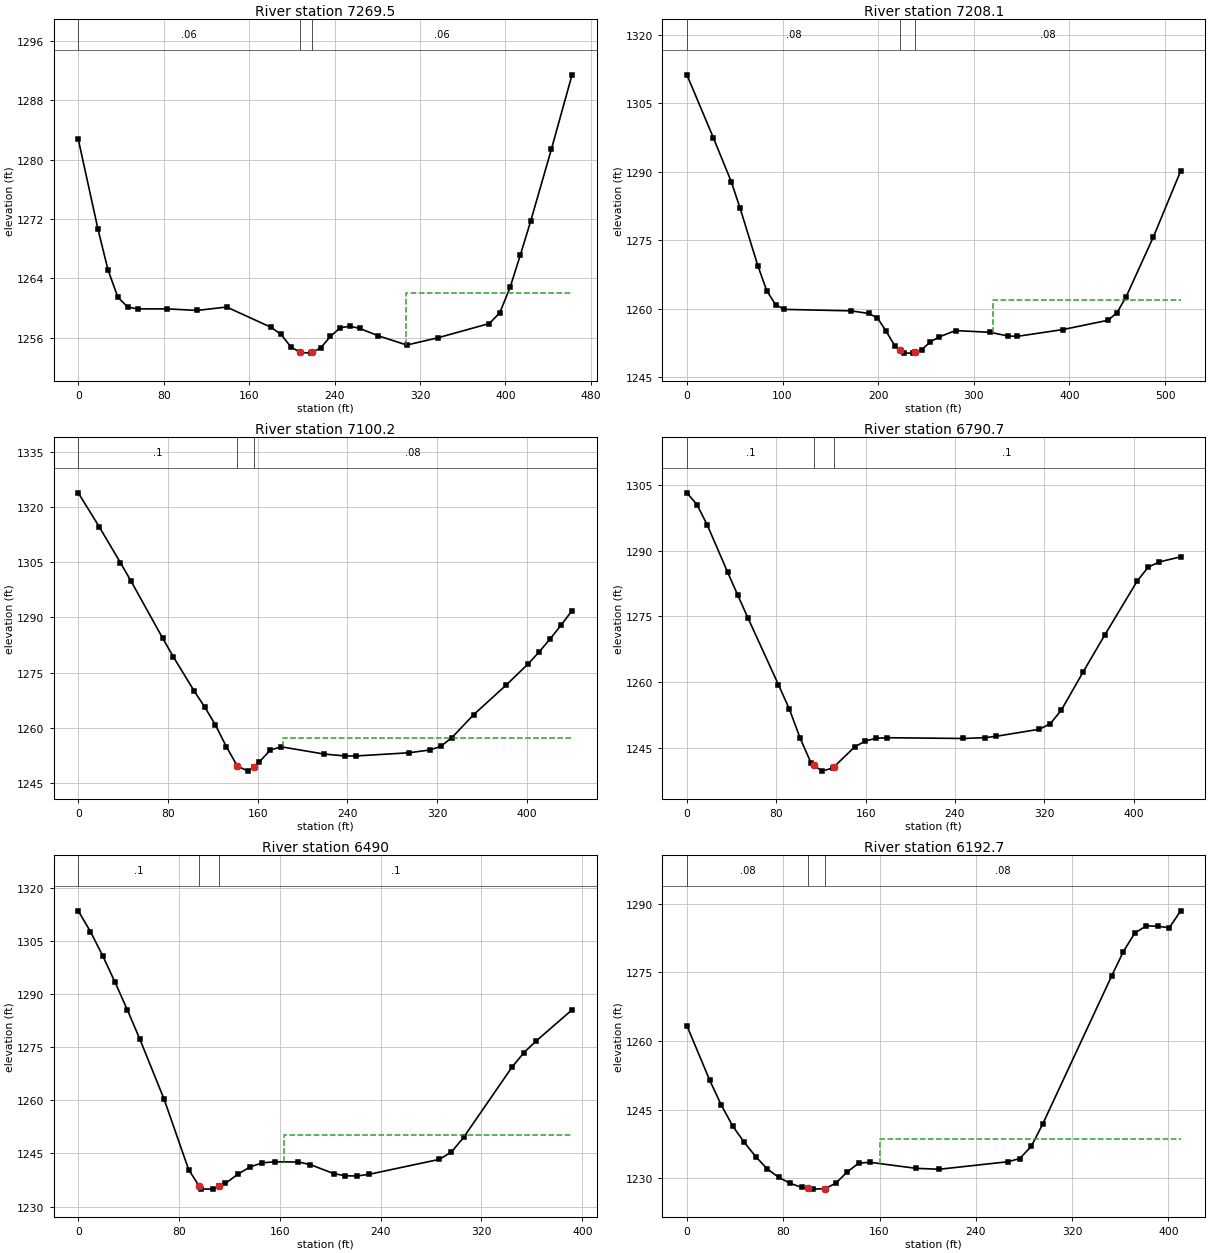
Type RM Length L Ch R = 1 ,7269.5  ,62.2,61.4,86.4
XS GIS Cut Line= 6
     1845562.879      365029.572     1845656.738      364926.993
     1845675.379      364940.683     1845755.587      364986.864
     1845797.948      365018.461     1845882.844      364888.947
#Sta/Elev= 30
       0 1282.77    18.5 1270.63    27.8 1265.19    37.1 1261.47    46.4 1260.14
    55.6  1259.9    83.4  1259.9   111.2 1259.69     139 1260.15   180.7 1257.41
   189.9 1256.46   199.2 1254.76     2081254.033   217.7 1253.94     2191254.037
     227 1254.63   236.2  1256.2   245.5 1257.38   254.7 1257.55   263.5 1257.27
   281.1 1256.27   307.6 1255.03   336.6    1256     385 1257.93   394.7 1259.37
   404.4 1262.81     414 1267.16   423.7 1271.74   443.1 1281.43   462.4 1291.43
#Mann= 3 , 0 , 0
       0     .06       0     208    .045       0     219     .06       0
#XS Ineff= 2 , 0
       0                     307       0    1262
Permanent Ineff=
       F       F
Bank Sta=208,219
XS Rating Curve= 0 ,0
Exp/Cntr=0.3,0.1

Type RM Length L Ch R = 1 ,7208.1  ,126,107.9,63
XS GIS Cut Line= 6
     1845543.695      365083.999     1845637.554      364981.421
     1845656.195       364995.11     1845736.403      365041.291
     1845778.764      365072.888     1845890.223      364896.326
#Sta/Elev= 30
       0 1311.22    27.8 1297.38    46.4 1287.83    55.6 1282.05    74.2 1269.44
    83.4 1264.03    92.7 1260.91     102  1259.9   171.4 1259.58   189.9 1259.02
   199.2 1258.05   208.4 1255.11   217.5 1251.89     2231250.987     227 1250.33
   236.2 1250.34     2391250.559   245.5 1251.07   254.7 1252.81   263.5 1253.86
   281.1 1255.27   317.1 1254.88     336 1254.07   345.5    1254     393 1255.48
   440.4 1257.52   449.9 1259.21   459.4  1262.7   487.9  1275.8   516.4 1290.21
#Mann= 3 , 0 , 0
       0     .08       0     223    .045       0     239     .08       0
#XS Ineff= 2 , 0
       0                     320       0    1262
Permanent Ineff=
       F       F
Bank Sta=223,239
XS Rating Curve= 0 ,0
Exp/Cntr=0.3,0.1

Type RM Length L Ch R = 1 ,7100.2  ,324.4,309.6,292.4
XS GIS Cut Line= 5
     1845666.733      365215.389      1845744.62      365121.005
     1845801.079      365104.455     1845930.622      365045.685
     1846010.049      364959.747
#Sta/Elev= 30
       0 1323.82    18.8 1314.57    37.6 1304.87    47.1 1299.86    75.3 1284.38
    84.7 1279.37   103.6 1269.94     113 1265.61   122.4 1260.79   132.2 1254.88
     142 1249.61   151.8 1248.28   156.5 1249.48   161.6 1250.79   171.4 1254.01
   181.2 1254.88   219.1 1252.92   238.1  1252.4   247.6  1252.4     295 1253.26
     314 1254.03   323.5 1255.03   333.2 1257.35   352.7 1263.59     382 1271.71
   401.5 1277.44   411.2 1280.65     421 1284.18   430.7 1287.89   440.5 1291.86
#Mann= 3 , 0 , 0
       0      .1       0     142    .045       0   156.5     .08       0
#XS Ineff= 2 , 0
       0                     183       0  1257.4
Permanent Ineff=
       F       F
Bank Sta=142,156.5
XS Rating Curve= 0 ,0
Exp/Cntr=0.3,0.1

Type RM Length L Ch R = 1 ,6790.7  ,298,300.7,302.3
XS GIS Cut Line= 3
     1845892.393      365425.145      1845947.81      365364.638
     1846145.171      365063.339
#Sta/Elev= 30
       0 1303.18     9.1 1300.46    18.2 1295.85    36.5 1285.06    45.6  1279.8
    54.7 1274.61      82 1259.39    91.8  1253.8   101.5 1247.15   111.2 1241.51
     114 1240.99     121 1239.69   130.7 1240.42   131.51240.614   150.2 1245.21
   159.9 1246.58   169.7 1247.19   179.4 1247.31   247.5 1247.14     267 1247.33
   276.7 1247.63   315.7 1249.25   325.4 1250.51   335.2 1253.57   354.6 1262.22
   374.1 1270.71   403.3 1283.08     413  1286.2   422.8  1287.4   442.2 1288.58
#Mann= 3 , 0 , 0
       0      .1       0     114    .045       0   131.5      .1       0
Bank Sta=114,131.5
XS Rating Curve= 0 ,0
Exp/Cntr=0.3,0.1

Type RM Length L Ch R = 1 ,6490    ,293.4,297.2,300.5
XS GIS Cut Line= 4
     1846139.615      365598.756     1846243.087      365469.589
     1846329.243      365384.392     1846404.198      365310.562
#Sta/Elev= 30
       0 1313.61     9.7 1307.74    19.5 1300.84    29.2 1293.44    38.9 1285.68
    48.7 1277.49    68.2  1260.3    87.6 1240.46    95.71235.921    97.4 1234.97
   107.1 1234.92   111.71235.685   116.8 1236.54   126.6 1239.11   136.3 1241.18
     146 1242.35   155.8 1242.65   174.8 1242.58   184.1 1241.86   202.8 1239.31
   212.1 1238.69   221.4 1238.64   230.7  1239.1   286.7 1243.34   296.2 1245.43
   305.8 1249.52   344.1 1269.34   353.6 1273.48   363.2 1276.74   391.9 1285.62
#Mann= 3 , 0 , 0
       0      .1       0    95.7    .045       0   111.7      .1       0
#XS Ineff= 2 , 0
                          162.98          1250.1
Permanent Ineff=
       F       F
Bank Sta=95.7,111.7
XS Rating Curve= 0 ,0
Exp/Cntr=0.3,0.1

Type RM Length L Ch R = 1 ,6192.7  ,151.5,152.4,153.2
XS GIS Cut Line= 3
     1846319.582      365813.004     1846432.276      365710.491
     1846638.815      365556.036
#Sta/Elev= 30
       0 1263.34      19 1251.38    28.6 1245.97    38.1 1241.37    47.6 1237.85
    57.1 1234.73    66.6 1232.06    76.2 1230.19    85.7 1228.87    95.2    1228
     1011227.754   104.7  1227.6     1151227.707   123.8 1228.93   133.3 1231.39
   142.8  1233.3   152.3 1233.46   190.6 1232.14   209.7 1231.95     267  1233.6
   276.5  1234.3   286.1 1236.96   295.6 1241.87   352.9 1274.27   362.5 1279.53
     372 1283.61   381.6  1285.2   391.1  1285.1   400.7 1284.78   410.2 1288.48
#Mann= 3 , 0 , 0
       0     .08       0     101    .045       0     115     .08       0
#XS Ineff= 2 , 0
                          160.76         1238.66
Permanent Ineff=
       F       F
Bank Sta=101,115
XS Rating Curve= 0 ,0
Exp/Cntr=0.3,0.1