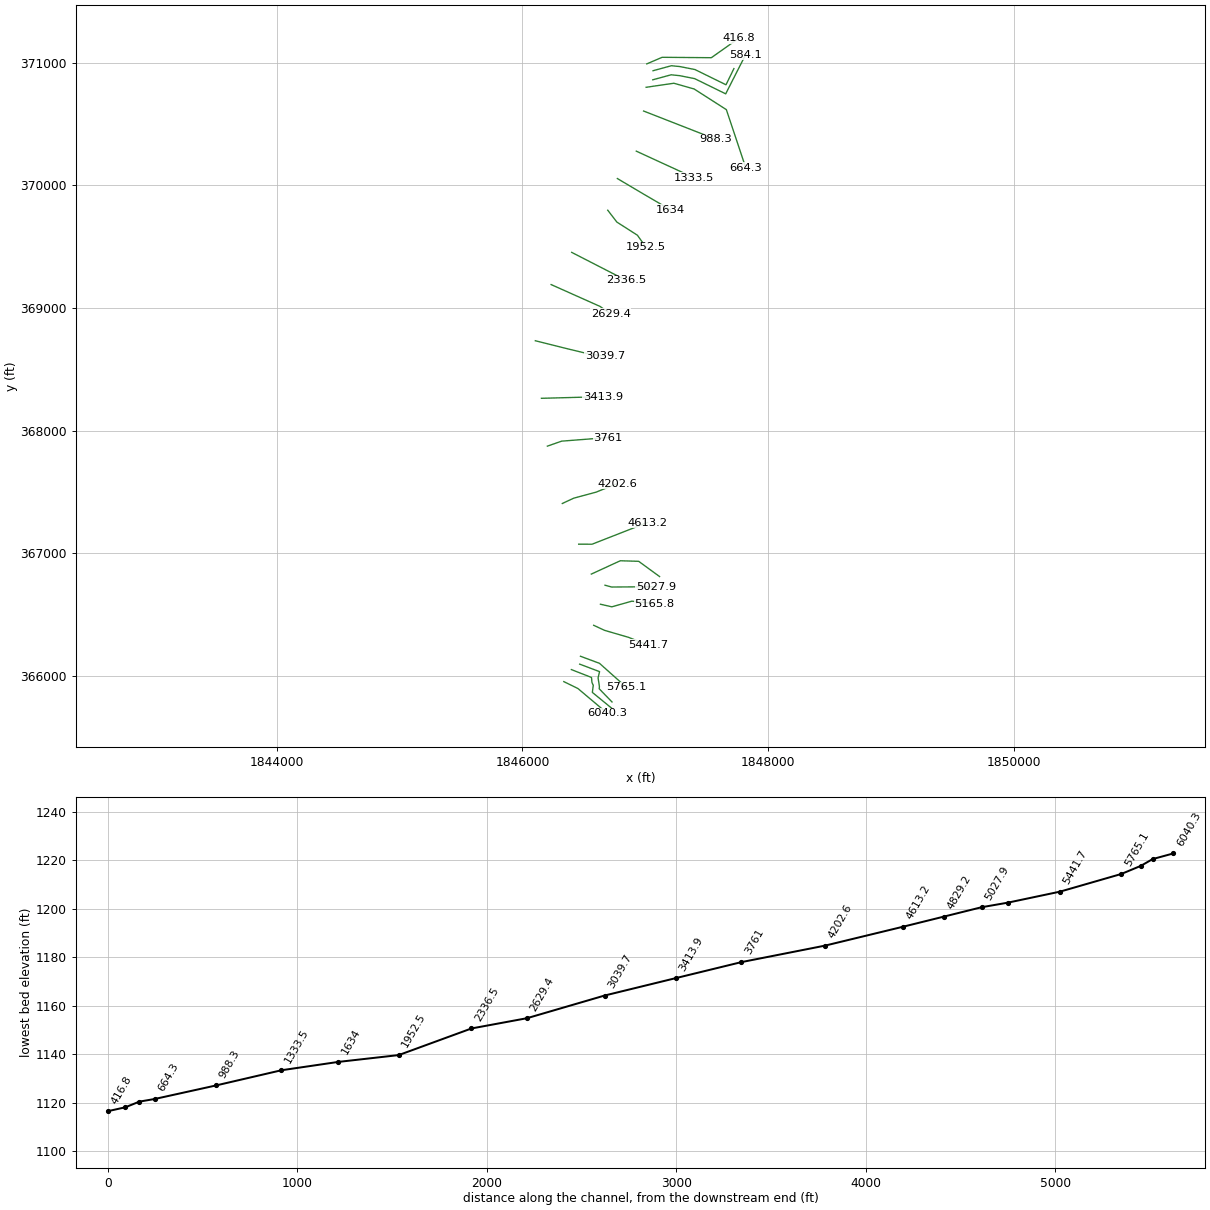
HEC-RAS study FIFTENMIFK.prj: FIFTENMIFK

--- FIFTENMIFK.g01 (geometry) --- (continued)

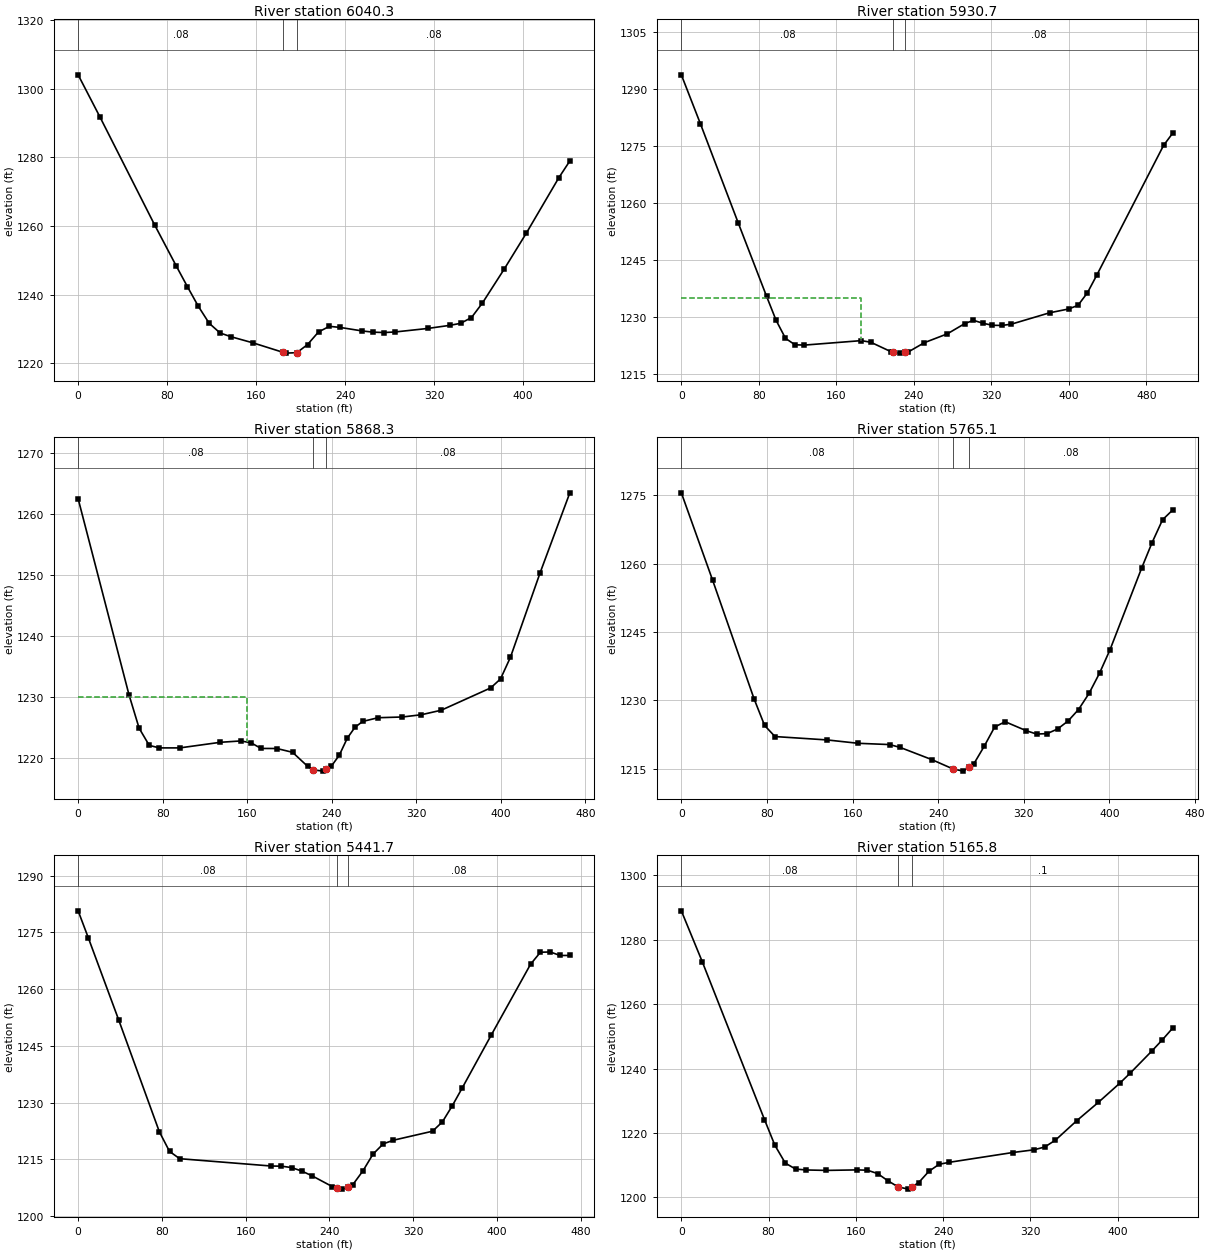
Type RM Length L Ch R = 1 ,6040.3  ,122.1,109.6,92.2
XS GIS Cut Line= 3
       1846336.8      365952.148     1846451.383      365895.898
     1846691.661       365693.12
#Sta/Elev= 30
       0 1304.02    19.6 1291.75    68.7 1260.33    88.4 1248.21    98.2 1242.32
     108  1236.6   117.8 1231.63   127.6  1228.8   137.5  1227.7   157.1 1225.93
   184.61223.122   186.6 1222.93   196.6 1223.06   206.2 1225.42   216.1 1229.11
   225.9 1230.74   235.7 1230.41   255.4 1229.39   265.2 1229.04     275 1228.93
   284.8 1229.09   314.3 1230.12     334 1231.02   343.8 1231.61   353.6  1233.3
   363.4 1237.52   383.1 1247.46   402.8 1257.84   432.2 1274.09     442 1278.92
#Mann= 3 , 0 , 0
       0     .08       0   184.6    .045       0   196.6     .08       0
Bank Sta=184.6,196.6
XS Rating Curve= 0 ,0
Exp/Cntr=0.3,0.1

Type RM Length L Ch R = 1 ,5930.7  ,71.7,62.4,61.6
XS GIS Cut Line= 6
     1846398.209      366050.319     1846562.046      365986.187
     1846565.725      365945.721     1846576.368      365921.951
      1846568.99      365864.225     1846728.336      365733.615
#Sta/Elev= 30
       0 1293.63    19.6 1280.84    58.6 1254.84      88 1235.48    97.8  1229.2
   107.5 1224.47   117.3 1222.78   127.1  1222.7   185.7 1223.87   195.5 1223.45
   216.8 1220.92   218.81220.846   225.5 1220.59   230.81220.779   234.2  1220.9
   250.8 1223.33   274.5 1225.65   292.5 1228.34   301.5  1229.2   311.3 1228.43
   321.1  1227.9   330.9 1227.85   340.7  1228.2     380 1231.17   399.6 1232.17
   409.4 1233.13   419.2 1236.46     429 1241.16   497.7  1275.1   507.5 1278.44
#Mann= 3 , 0 , 0
       0     .08       0   218.8    .045       0   230.8     .08       0
#XS Ineff= 2 , 0
       0   185.7    1235               0
Permanent Ineff=
       F       F
Bank Sta=218.8,230.8
XS Rating Curve= 0 ,0
Exp/Cntr=0.3,0.1

Type RM Length L Ch R = 1 ,5868.3  ,80.2,103.2,119.7
XS GIS Cut Line= 6
     1846465.836      366094.813     1846627.728      366033.615
     1846615.576      365984.136     1846626.426      365911.219
      1846624.69      365893.858     1846728.857      365786.219
#Sta/Elev= 30
       0 1262.47    48.1 1230.34    57.7 1224.84    67.3 1222.01    76.9  1221.6
    96.2  1221.6   134.6 1222.52   153.8 1222.74   163.5 1222.45   173.1 1221.51
     188  1221.5   202.9 1220.88   217.1 1218.59   222.71217.991   231.9 1217.79
   234.71218.077   239.5 1218.57   247.1 1220.39   254.7 1223.19     262 1224.99
   269.3 1225.94   283.8 1226.55   306.8 1226.67   324.8 1227.04   343.6 1227.78
   390.4 1231.44   399.7 1232.91   409.1 1236.47   437.2 1250.34   465.3 1263.44
#Mann= 3 , 0 , 0
       0     .08       0   222.7    .045       0   234.7     .08       0
#XS Ineff= 2 , 0
       0     160    1230               0
Permanent Ineff=
       F       F
Bank Sta=222.7,234.7
XS Rating Curve= 0 ,0
Exp/Cntr=0.3,0.1

Type RM Length L Ch R = 1 ,5765.1  ,311.5,323.4,331.9
XS GIS Cut Line= 3
     1846472.216      366159.092     1846627.077      366101.454
     1846846.522       365905.62
#Sta/Elev= 30
       0 1275.53    29.2 1256.36      68 1230.27    77.8 1224.45    87.5 1222.02
   136.1 1221.28   165.2 1220.54   194.6 1220.26   204.5 1219.63   233.9 1216.97
   253.5 1214.94   263.3 1214.43   268.51215.239   273.1 1215.96   282.9 1219.86
   292.7  1224.1   302.5 1225.28   322.1 1223.32   331.9 1222.57   341.7 1222.66
   351.5 1223.68   361.3 1225.43   371.1 1227.96   380.9 1231.49   390.7 1235.93
   400.5 1241.08     430 1258.97   439.8  1264.6   449.6 1269.62   459.4 1271.84
#Mann= 3 , 0 , 0
       0     .08       0   253.5    .045       0   268.5     .08       0
Bank Sta=253.5,268.5
XS Rating Curve= 0 ,0
Exp/Cntr=0.3,0.1

Type RM Length L Ch R = 1 ,5441.7  ,261.4,275.9,287.9
XS GIS Cut Line= 4
     1846579.946      366411.701     1846667.854      366370.631
     1846863.749      366313.421     1847020.224       366250.59
#Sta/Elev= 30
       0 1280.73     9.7 1273.62    38.8 1251.84    77.6 1222.29    87.3 1217.11
      97 1215.18   184.5 1213.24   194.2  1213.2   203.9 1212.83   213.6 1211.91
   223.4 1210.66   242.8  1207.8   247.2  1207.5   252.5 1207.13   258.21207.782
   262.2 1208.24     272 1211.93   281.7 1216.39   291.4 1219.09   301.1 1220.06
   338.6 1222.45     348 1224.93   357.3 1229.12   366.7 1233.78   394.8 1247.96
   432.2 1266.61   441.6 1269.78     451 1269.85   460.4 1268.92   469.7 1268.93
#Mann= 3 , 0 , 0
       0     .08       0   247.2    .045       0   258.2     .08       0
Bank Sta=247.2,258.2
XS Rating Curve= 0 ,0
Exp/Cntr=0.3,0.1

Type RM Length L Ch R = 1 ,5165.8  ,143.6,137.9,131.4
XS GIS Cut Line= 4
     1846634.754      366583.478     1846727.676      366562.423
     1846890.504      366608.486     1847075.726      366589.034
#Sta/Elev= 30
       0 1288.95    19.1 1273.22    76.2 1224.16    85.8 1216.13    95.3 1210.65
   104.7  1208.8   114.1 1208.52   132.9 1208.38   161.1 1208.54   170.5 1208.44
   179.9  1207.4   189.3 1205.17   198.7 1203.26   208.1 1202.57   211.7 1203.34
   217.5 1204.58   226.9  1208.1   236.3 1210.28   245.7  1210.9   303.7 1213.93
   323.3 1214.78   333.1 1215.65   342.9 1217.78   362.5 1223.83   382.1 1229.46
   401.7 1235.39   411.5  1238.6   431.1 1245.38   440.9 1248.91   450.7 1252.68
#Mann= 3 , 0 , 0
       0     .08       0   198.7    .045       0   211.7      .1       0
Bank Sta=198.7,211.7
XS Rating Curve= 0 ,0
Exp/Cntr=0.3,0.1

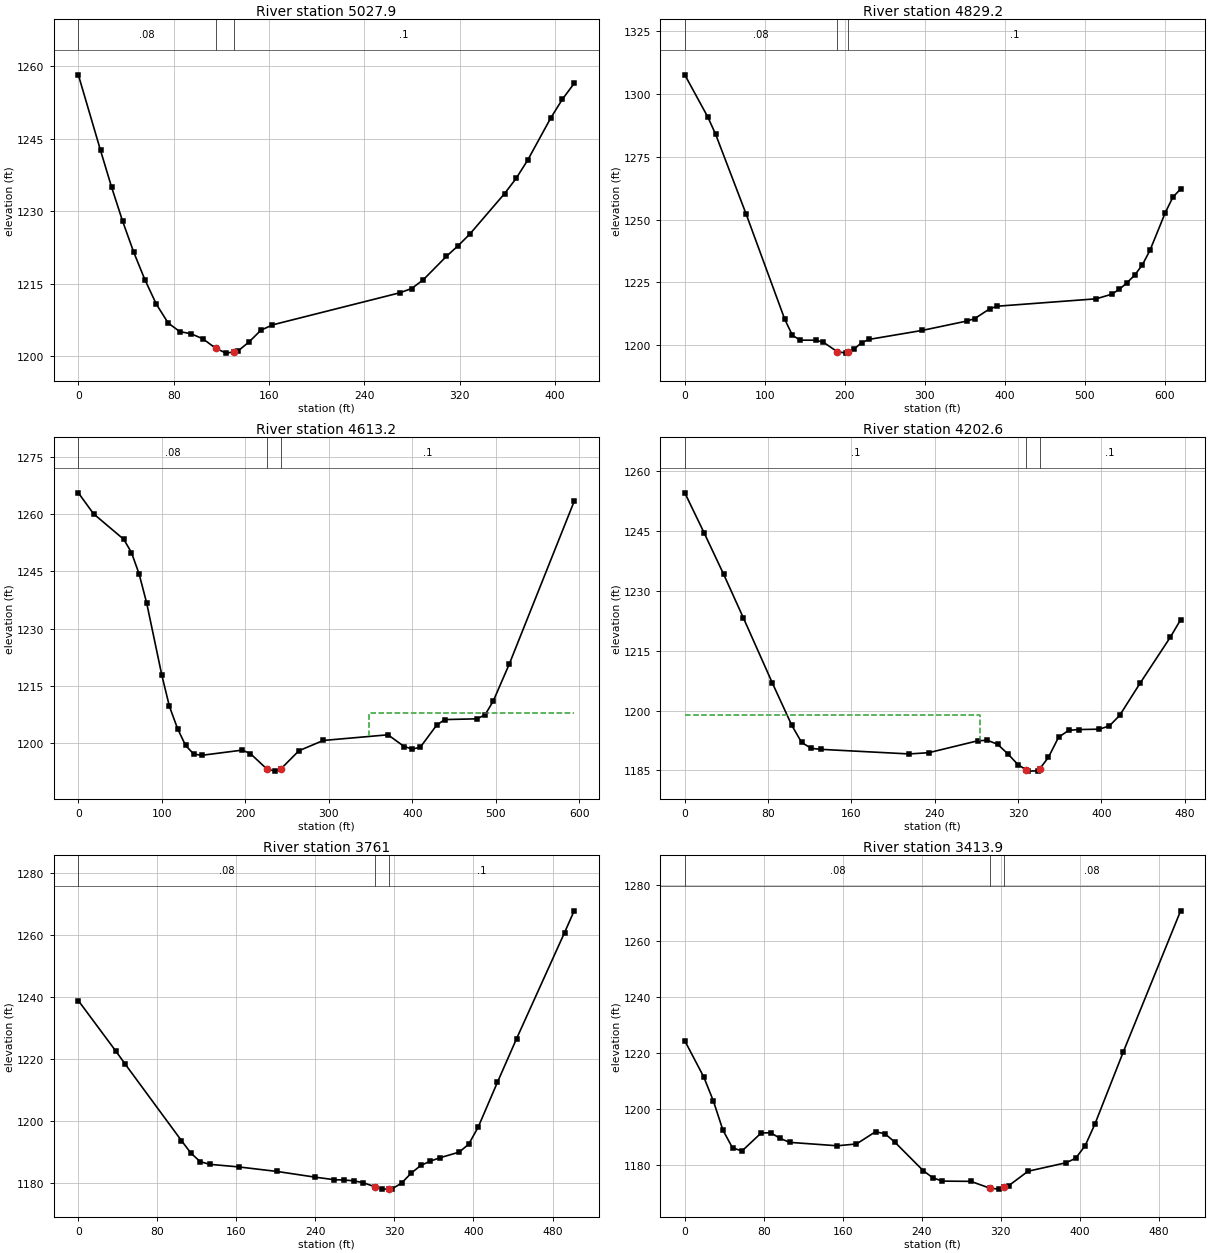
Type RM Length L Ch R = 1 ,5027.9  ,188.7,198.6,207.9
XS GIS Cut Line= 3
     1846672.169      366738.559     1846725.991      366723.857
     1847086.051      366726.334
#Sta/Elev= 30
       0 1258.27    18.6 1242.65    27.9 1235.03    37.2 1227.95    46.5 1221.55
    55.8  1215.9    65.5 1210.79    75.3 1206.94      85 1205.16    94.7 1204.68
   104.4 1203.66   115.21201.703   123.9 1200.69   130.21200.936   133.6 1201.07
   143.4 1203.05   153.1 1205.42   162.8 1206.53   269.9 1213.19   279.6 1214.06
   289.4 1215.88   308.8 1220.73   318.6 1222.92   328.3  1225.3   357.5 1233.69
   367.2 1236.83   376.9 1240.61   396.4  1249.4   406.1 1253.24   415.9  1256.5
#Mann= 3 , 0 , 0
       0     .08       0   115.2    .045       0   130.2      .1       0
Bank Sta=115.2,130.2
XS Rating Curve= 0 ,0
Exp/Cntr=0.3,0.1

Type RM Length L Ch R = 1 ,4829.2  ,216.8,216,214.2
XS GIS Cut Line= 4
     1846560.593      366829.393     1846796.415      366938.132
      1846946.01       366933.56     1847116.149      366809.254
#Sta/Elev= 30
       0 1307.72    28.8 1290.89    38.5 1284.07    76.9 1252.07     125 1210.31
   134.6  1203.9   144.3    1202   163.5 1201.96   173.1 1201.22   190.61197.399
     202 1196.82   204.6 1197.25   211.6 1198.39   221.2 1201.01   230.8 1202.31
   297.1 1205.88   353.2 1209.64   362.6 1210.59   381.3 1214.47   390.6 1215.51
   514.7 1218.47   533.9  1220.3   543.4 1222.24     553 1224.84   562.6 1227.89
   572.2 1231.96   581.8 1237.81   600.9 1252.79   610.5 1259.02   620.1 1262.21
#Mann= 3 , 0 , 0
       0     .08       0   190.6    .045       0   204.6      .1       0
Bank Sta=190.6,204.6
XS Rating Curve= 0 ,0
Exp/Cntr=0.3,0.1

Type RM Length L Ch R = 1 ,4613.2  ,409.2,410.6,409.7
XS GIS Cut Line= 3
     1846457.618      367073.216      1846566.69      367073.105
     1847017.818      367250.039
#Sta/Elev= 30
       0 1265.63    18.2 1260.13    54.5 1253.41    63.6 1249.96    72.7  1244.4
    81.8 1236.76     100 1217.76   109.1 1209.59   118.8 1203.79   128.4 1199.37
   138.2  1197.1   147.8 1196.78   196.3 1198.14     206 1197.23   225.4 1193.26
   235.1 1192.63   242.9 1193.29   264.1 1197.97   293.2 1200.67   370.8 1202.16
   390.1 1199.09   399.8 1198.42   409.5  1198.9   428.9 1204.65   438.6 1206.15
   477.4 1206.35     487  1207.4   496.7 1210.95   516.1 1220.76   593.7 1263.39
#Mann= 3 , 0 , 0
       0     .08       0   225.4    .045       0   242.9      .1       0
#XS Ineff= 2 , 0
                          347.56         1207.96
Permanent Ineff=
       F       F
Bank Sta=225.4,242.9
XS Rating Curve= 0 ,0
Exp/Cntr=0.3,0.1

Type RM Length L Ch R = 1 ,4202.6  ,447.4,441.6,433.5
XS GIS Cut Line= 4
     1846324.459      367405.204     1846417.578      367448.851
     1846598.872      367497.653     1846770.918      367567.256
#Sta/Elev= 30
       0 1254.64    18.7 1244.52    37.4 1234.16    56.1 1223.36    84.1 1206.93
   102.8 1196.31   112.2 1192.03   121.6 1190.54     131  1190.3   215.5 1189.15
   234.3 1189.46   281.2 1192.44   290.6 1192.58   300.4 1191.57   310.1 1189.22
   319.9  1186.5     3281185.128   329.7 1184.84   339.4 1184.91     3411185.462
   349.2 1188.29     359 1193.34   368.7 1195.07   378.5 1195.27     398 1195.36
   407.8 1196.18   417.6  1198.8   437.1 1206.82   466.4 1218.47   476.2  1222.8
#Mann= 3 , 0 , 0
       0      .1       0     328    .045       0     341      .1       0
#XS Ineff= 2 , 0
          283.88 1198.88
Permanent Ineff=
       F       F
Bank Sta=328,341
XS Rating Curve= 0 ,0
Exp/Cntr=0.3,0.1

Type RM Length L Ch R = 1 ,3761    ,347.2,347.1,345
XS GIS Cut Line= 3
     1846202.714      367873.086     1846319.104      367913.851
      1846696.49      367943.383
#Sta/Elev= 30
       0 1238.76      38 1222.46    47.4 1218.31   104.4 1193.64   113.8 1189.68
   123.3 1186.88     133 1186.01   162.2 1185.18     201 1183.72   239.8 1181.87
   259.2 1181.05   268.9 1180.96   278.6  1180.7   288.3  1180.1     3001178.797
   307.7 1178.02     3141178.059   317.4 1178.08   327.2 1179.96   336.9 1183.16
   346.6 1185.64   356.3 1187.03     366 1188.12   385.4 1189.93   395.1 1192.47
   404.8 1198.03   424.2 1212.42   443.6 1226.49   492.2 1260.68   501.9 1267.68
#Mann= 3 , 0 , 0
       0     .08       0     300    .045       0     314      .1       0
Bank Sta=300,314
XS Rating Curve= 0 ,0
Exp/Cntr=0.3,0.1

Type RM Length L Ch R = 1 ,3413.9  ,379.8,374.3,367.9
XS GIS Cut Line= 2
     1846154.465      368263.351     1846656.256      368276.948
#Sta/Elev= 30
       0  1224.3    19.3 1211.32      29 1202.76    38.6 1192.42    48.3 1186.12
    57.9 1184.99    77.2 1191.38    86.9 1191.52    96.5 1189.49   106.2 1188.07
   154.4 1186.85   173.8  1187.5   193.1 1191.86   202.7 1191.13   212.4 1188.23
   241.3 1178.01     251 1175.46   260.6 1174.25   289.6 1174.16     3091171.717
   318.6 1171.39     3231171.983   328.2 1172.68   347.5 1177.77   386.1 1180.81
   395.8  1182.4   405.4 1186.93   415.1 1194.49     444 1220.37     502 1270.65
#Mann= 3 , 0 , 0
       0     .08       0     309    .045       0     323     .08       0
Bank Sta=309,323
XS Rating Curve= 0 ,0
Exp/Cntr=0.3,0.1

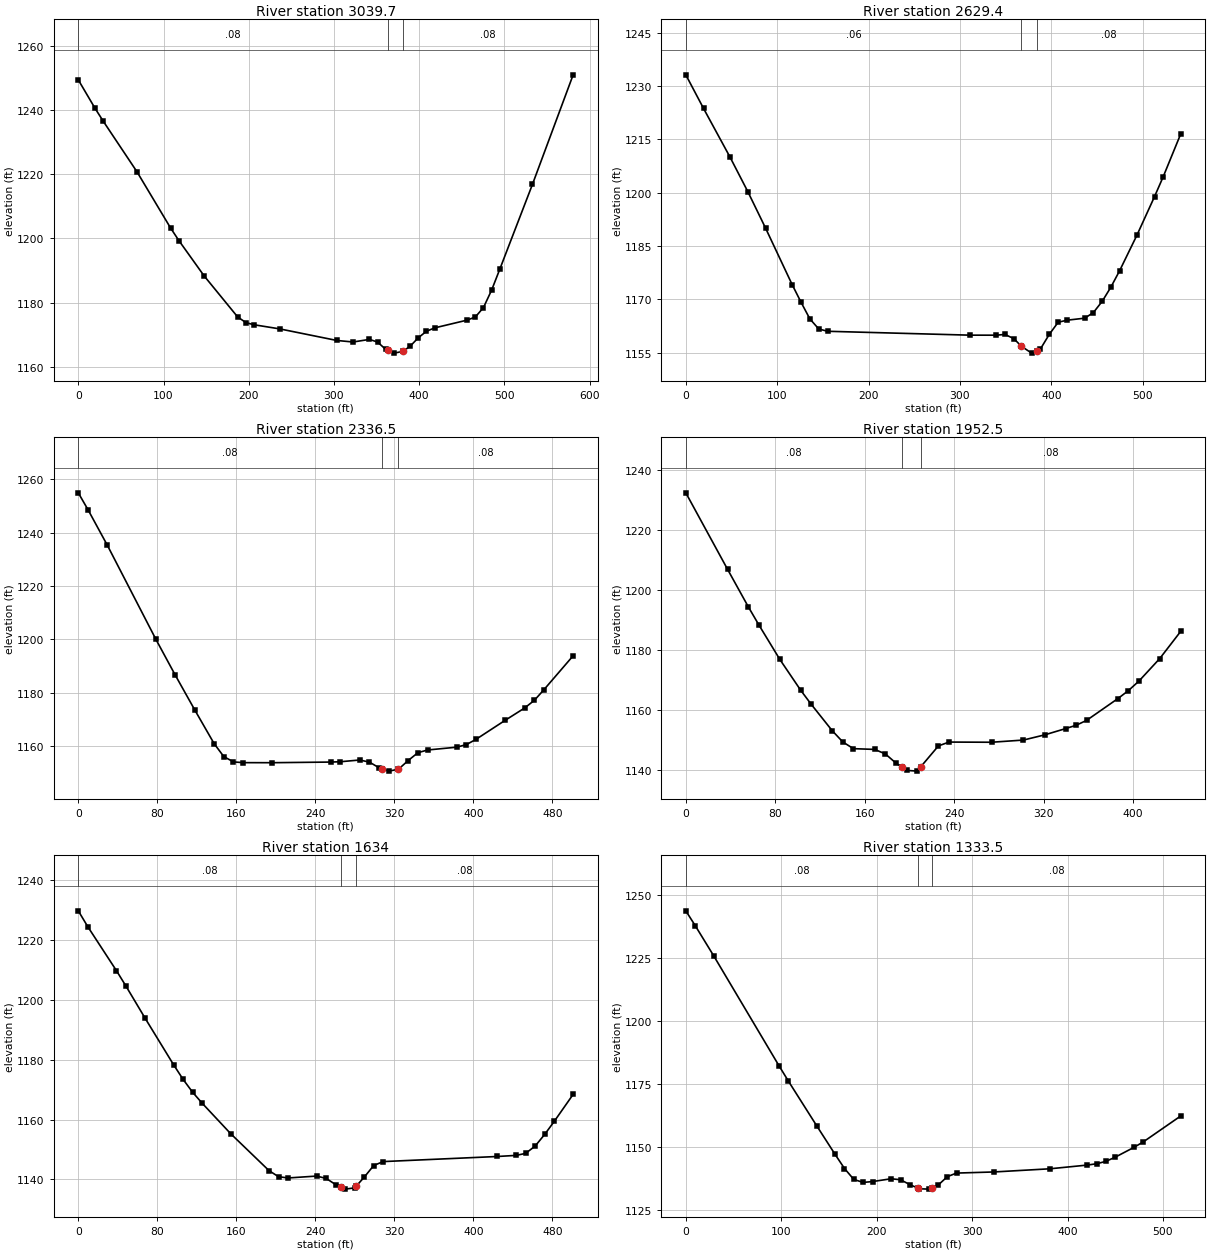
Type RM Length L Ch R = 1 ,3039.7  ,413.6,410.3,405.3
XS GIS Cut Line= 4
     1846104.731      368732.941     1846343.262      368673.056
      1846547.72       368623.42     1846671.137      368609.243
#Sta/Elev= 30
       0 1249.44    19.7 1240.55    29.5 1236.46    68.9 1220.76   108.2 1203.28
     118 1199.33   147.6 1188.32   186.9 1175.53   196.8 1173.71   206.6 1173.05
   236.1 1171.79   303.3 1168.17   322.4 1167.69   341.6  1168.5   351.1 1167.68
   360.7 1165.39   363.21165.084   370.3 1164.22   380.71164.735   389.4 1166.39
     399 1169.03   408.5 1171.04   418.1 1172.09   456.3 1174.52   465.9  1175.5
   475.4 1178.44     485  1183.9   494.6 1190.44   532.8 1216.81   580.6 1251.01
#Mann= 3 , 0 , 0
       0     .08       0   363.2    .045       0   380.7     .08       0
Bank Sta=363.2,380.7
XS Rating Curve= 0 ,0
Exp/Cntr=0.3,0.1

Type RM Length L Ch R = 1 ,2629.4  ,293.1,292.9,290.7
XS GIS Cut Line= 3
     1846233.358      369191.133     1846631.861      369012.816
     1846717.446      368951.979
#Sta/Elev= 30
       0 1233.19    19.4 1223.73    48.5 1209.97    67.9 1200.29    87.3 1190.03
   116.4 1174.12   126.1 1169.17   135.8 1164.47   145.5 1161.64   155.2 1160.99
   310.5  1159.9   339.6 1159.89   349.3  1160.1     359 1158.92     3671156.842
   378.4 1154.84     384 1155.51   388.1    1156   397.8 1160.12   407.5 1163.53
   417.2 1164.11   436.6 1164.68   446.1 1166.27   455.7 1169.42   465.2 1173.41
   474.8 1178.05   493.9 1188.14     513 1198.91   522.5 1204.51   541.6 1216.52
#Mann= 3 , 0 , 0
       0     .06       0     367    .045       0     384     .08       0
Bank Sta=367,384
XS Rating Curve= 0 ,0
Exp/Cntr=0.3,0.1

Type RM Length L Ch R = 1 ,2336.5  ,384.9,384,380.6
XS GIS Cut Line= 2
     1846400.799       369453.86      1846846.26      369224.825
#Sta/Elev= 30
       0 1254.98     9.8 1248.67    29.5 1235.25    78.6    1200    98.2 1186.58
   117.9 1173.55   137.5 1160.91   147.3 1156.05   157.1 1154.06     167 1153.78
   196.4 1153.76   255.4    1154   265.2 1154.12   284.8 1154.77   294.6    1154
   304.5 1151.85   307.1 1151.52   314.3  1150.6   324.1 1151.31   333.9 1154.57
   343.8 1157.52   353.6 1158.53     383 1159.58   392.9 1160.56   402.7 1162.55
   432.1 1169.66   451.8 1174.28   461.6 1177.14   471.4 1181.17   500.9 1193.87
#Mann= 3 , 0 , 0
       0     .08       0   307.1    .045       0   324.1     .08       0
Bank Sta=307.1,324.1
XS Rating Curve= 0 ,0
Exp/Cntr=0.3,0.1

Type RM Length L Ch R = 1 ,1952.5  ,315.5,318.5,317.3
XS GIS Cut Line= 4
     1846694.347      369797.638     1846768.186      369701.223
     1846936.073      369593.534     1847006.153      369494.166
#Sta/Elev= 30
       0 1232.39    37.4 1206.84      56 1194.31    65.4  1188.3    84.1 1176.83
   102.8 1166.53   112.1  1161.9   130.9 1153.09   140.4 1149.32   149.9 1147.09
   168.9 1146.84   178.4 1145.34   187.9 1142.28   193.31140.901   197.4 1139.85
   206.9  1139.6   210.3 1141.14   225.9 1148.02   235.4 1149.29   273.4 1149.23
   301.9 1149.96   320.9 1151.69   339.6 1153.78     349 1154.89   358.3  1156.5
   386.4  1163.8   395.7 1166.43   405.1 1169.59   423.8 1177.14   442.5 1186.18
#Mann= 3 , 0 , 0
       0     .08       0   193.3    .045       0   210.3     .08       0
Bank Sta=193.3,210.3
XS Rating Curve= 0 ,0
Exp/Cntr=0.3,0.1

Type RM Length L Ch R = 1 ,1634    ,297.4,300.5,301.9
XS GIS Cut Line= 3
     1846772.599      370056.179     1846988.385      369928.009
     1847204.192      369801.714
#Sta/Elev= 30
       0 1229.74     9.6 1224.45    38.6 1209.77    48.3 1204.58    67.6  1193.9
    96.5 1178.32   106.2  1173.4   115.8 1169.12   125.5 1165.45   154.4 1155.26
   193.1 1142.96   202.7 1140.93   212.4 1140.51   241.3 1141.14     251 1140.35
   260.6 1138.28   265.51137.513   270.2 1136.78   279.8  1137.2   281.5 1137.83
   289.4 1140.74   299.1 1144.67   308.7 1145.98   424.1 1147.68   443.3 1148.05
   452.9 1148.72   462.6 1151.19   472.2 1155.06   481.8 1159.38     501 1168.43
#Mann= 3 , 0 , 0
       0     .08       0   265.5    .045       0   281.5     .08       0
Bank Sta=265.5,281.5
XS Rating Curve= 0 ,0
Exp/Cntr=0.3,0.1

Type RM Length L Ch R = 1 ,1333.5  ,342.9,345.2,345.6
XS GIS Cut Line= 2
     1846926.744      370279.516     1847397.694       370062.49
#Sta/Elev= 30
       0  1243.6     9.8 1237.77    29.4 1225.67    97.8 1182.12   107.6 1176.07
     137 1158.53   156.5 1147.06   166.3  1141.5   176.1 1137.15   185.9 1135.99
   195.7 1136.33   215.2 1137.44     225 1137.05   234.8 1135.12   243.41133.681
   244.6 1133.48   254.4 1133.33   258.41133.941   264.2 1134.83     274 1138.26
   283.7 1139.69   322.9 1140.13   381.6 1141.39   420.7 1142.86   430.5 1143.38
   440.3 1144.34   450.1 1146.01   469.6 1149.87   479.4 1152.04   518.6  1162.3
#Mann= 3 , 0 , 0
       0     .08       0   243.4    .045       0   258.4     .08       0
Bank Sta=243.4,258.4
XS Rating Curve= 0 ,0
Exp/Cntr=0.3,0.1

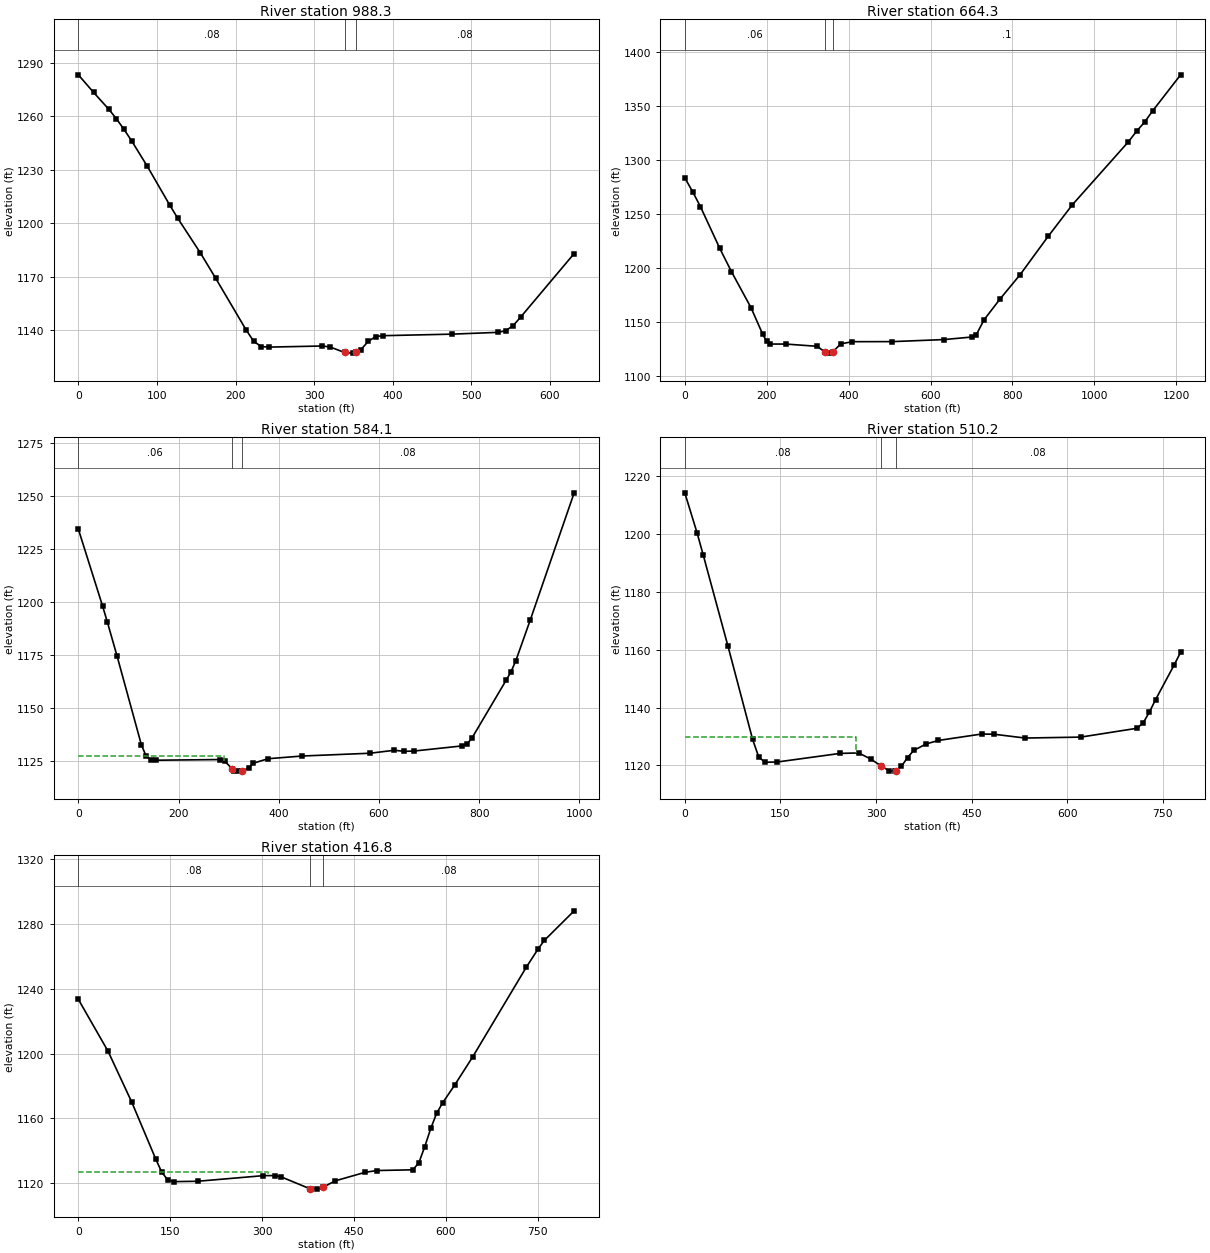
Type RM Length L Ch R = 1 ,988.3   ,321.2,323.9,325.6
XS GIS Cut Line= 2
     1846986.155       370606.97     1847573.529      370376.851
#Sta/Elev= 30
       0 1283.14    19.4 1273.29    38.8  1263.8    48.5 1258.47    58.2 1252.48
    67.9 1246.04    87.4  1232.1   116.5 1209.92   126.2 1202.88   155.3 1183.23
   174.7 1169.06   213.5 1140.03   223.2 1133.64   232.9 1130.71   242.6 1130.43
   310.6 1131.05   320.3  1130.5   338.71127.404   349.4 1127.05   353.71127.822
   359.1 1128.79   368.8 1133.64   378.5 1136.37   388.2 1136.84   475.6  1137.7
   533.8  1138.7   543.5 1139.58   553.2  1142.5   562.9 1147.35   630.8  1182.9
#Mann= 3 , 0 , 0
       0     .08       0   338.7    .045       0   353.7     .08       0
Bank Sta=338.7,353.7
XS Rating Curve= 0 ,0
Exp/Cntr=0.3,0.1

Type RM Length L Ch R = 1 ,664.3   ,78.3,80.3,82
XS GIS Cut Line= 5
     1847007.011      370800.582     1847232.705      370833.568
     1847397.636      370786.693     1847659.789       370618.29
     1847817.775      370144.332
#Sta/Elev= 30
       0 1283.45      19 1270.74      38 1256.94    85.5 1218.18     114 1196.69
   161.6 1163.51   190.1 1139.03   199.6 1132.48   209.1 1129.85   247.1 1129.82
   323.4 1127.75   342.4 1122.34   351.9 1121.45   361.4 1122.52   380.5 1129.97
   409.3 1132.03   506.7 1132.09   633.2 1133.98   701.4 1136.36   711.1 1137.95
   730.7 1152.26   769.9 1171.53   818.9 1194.02   887.5  1229.5   946.2 1258.49
  1083.4 1316.86    1103 1326.47  1122.6 1334.87  1142.2 1345.26  1210.7 1378.65
#Mann= 3 , 0 , 0
       0     .06       0   342.4    .045       0   361.4      .1       0
Bank Sta=342.4,361.4
XS Rating Curve= 0 ,0
Exp/Cntr=0.3,0.1

Type RM Length L Ch R = 1 ,584.1   ,73.6,73.9,73.6
XS GIS Cut Line= 6
     1847060.743      370861.628     1847210.049      370902.427
     1847279.493      370895.482     1847401.889      370871.177
     1847654.493      370747.045     1847816.907      371067.075
#Sta/Elev= 30
       0 1234.51    48.4 1198.23      58 1190.61    77.4 1174.57   125.8 1132.82
   135.4 1127.38   145.1 1125.75   154.8 1125.51   282.2 1125.83   291.8 1125.24
   306.91121.428     311 1120.48   320.6 1120.37   327.4 1120.49   339.8 1121.85
   349.4 1124.11   378.5 1126.22   446.4 1127.49   582.3 1128.81   630.8 1130.21
   650.2 1129.71   669.6 1129.83   766.6 1132.28   776.3  1133.2     786 1136.09
   853.9 1163.23   863.6  1167.2   873.3 1172.46   902.4 1191.86   989.7 1251.62
#Mann= 3 , 0 , 0
       0     .06       0   306.9    .045       0   327.4     .08       0
#XS Ineff= 2 , 0
       0     290 1127.34               0
Permanent Ineff=
       F       F
Bank Sta=306.9,327.4
XS Rating Curve= 0 ,0
Exp/Cntr=0.3,0.1

Type RM Length L Ch R = 1 ,510.2   ,88.9,93.4,97.5
XS GIS Cut Line= 6
     1847063.174      370935.673      1847212.48      370976.472
     1847281.924      370969.527      1847404.32      370945.222
     1847656.924       370821.09     1847721.421      370953.143
#Sta/Elev= 30
       0 1214.24    19.4 1200.29      29 1192.67    67.7 1161.25   106.4 1128.98
   116.1 1122.84   125.8 1121.11   145.1 1121.19   243.8 1124.16   272.6 1124.32
   291.8  1122.2   307.51119.858   320.6 1118.14   329.8 1118.03     3311118.166
   339.8 1119.66   349.4 1122.73   359.1 1125.18   378.5 1127.42   397.9 1128.64
   465.8 1130.86   485.2 1130.78   533.8 1129.47   621.1 1129.79   709.2 1132.84
     719 1134.67   728.8 1138.44   738.6 1142.79     768 1154.88   777.8 1159.14
#Mann= 3 , 0 , 0
       0     .08       0   307.5    .045       0     331     .08       0
#XS Ineff= 2 , 0
       0     268    1130               0
Permanent Ineff=
       F       F
Bank Sta=307.5,331
XS Rating Curve= 0 ,0
Exp/Cntr=0.3,0.1

Type RM Length L Ch R = 1 ,416.8   ,276.9,287.6,296.1
XS GIS Cut Line= 4
     1847012.219      370991.554     1847137.217      371045.127
      1847537.65      371041.931     1847760.483      371199.887
#Sta/Elev= 30
       0 1233.43    48.6 1201.37    87.4 1169.89   126.3 1135.04     136 1127.01
   145.8  1122.1   155.5 1121.02   194.6 1121.24     302 1124.71   321.6 1124.76
   331.3 1123.94   378.2 1116.62   380.2  1116.4   389.9  1116.4   399.7 1117.59
   419.2 1121.47   468.1 1126.75   487.6 1127.87   546.2 1128.31     556 1132.65
   565.7 1142.62   575.5 1153.89   585.2 1163.28     595  1169.7   614.5 1180.55
   643.8 1197.86   731.5 1253.27     751 1264.62   760.8 1269.72   809.6    1288
#Mann= 3 , 0 , 0
       0     .08       0   378.2    .045       0   399.7     .08       0
#XS Ineff= 2 , 0
          309.61 1126.87
Permanent Ineff=
       F       F
Bank Sta=378.2,399.7
XS Rating Curve= 0 ,0
Exp/Cntr=0.3,0.1