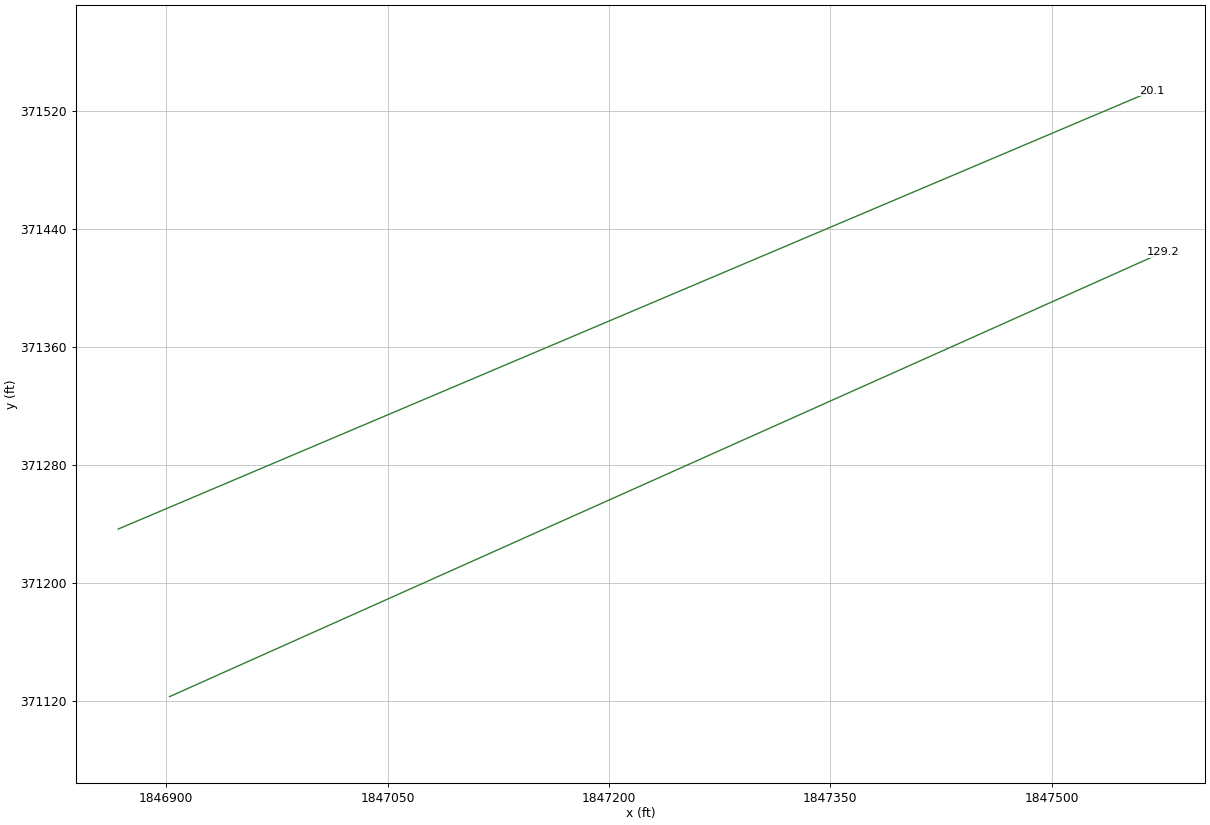
HEC-RAS study FIFTENMIFK.prj: FIFTENMIFK

--- FIFTENMIFK.g01 (geometry) --- (continued)

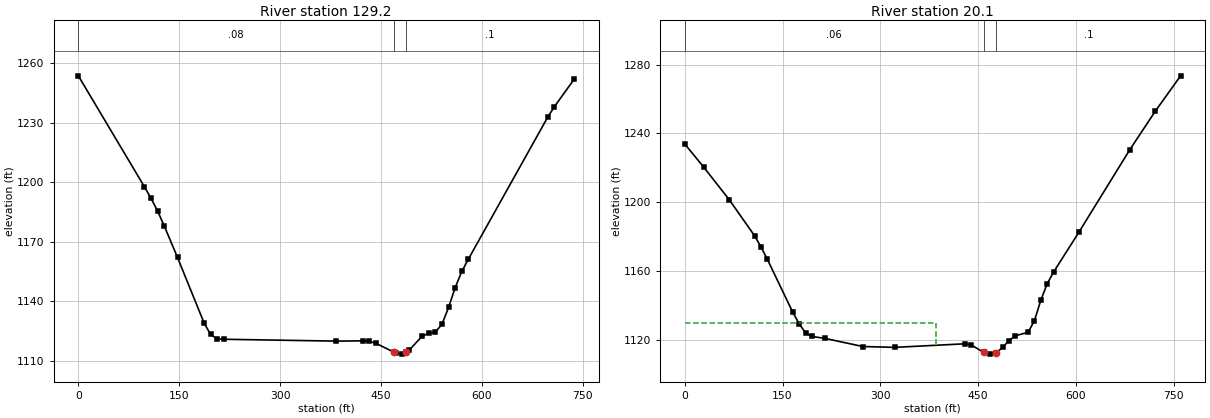
Type RM Length L Ch R = 1 ,129.2   ,109.3,109,108.5
XS GIS Cut Line= 2
     1846902.259      371123.123     1847575.304      371424.222
#Sta/Elev= 30
       0 1253.51    98.3 1197.66   108.1 1191.85     118 1185.34   127.8 1177.91
   147.5 1162.07   186.8 1129.27   196.6 1123.32   206.4 1121.09   216.3 1120.91
   383.4 1119.98   422.7 1120.12   432.6 1119.86   442.4 1118.91     469 1114.43
   471.9 1113.96   481.7 1113.43   487.5 1114.52   491.6 1115.29   511.2 1122.45
     521 1123.88   530.9 1124.55   540.7 1128.42   550.5  1136.9   560.4 1146.92
   570.2 1155.03     580 1161.25     698 1232.72   707.8 1237.92   737.3 1251.83
#Mann= 3 , 0 , 0
       0     .08       0     469    .045       0   487.5      .1       0
Bank Sta=469,487.5
XS Rating Curve= 0 ,0
Exp/Cntr=0.3,0.1

Type RM Length L Ch R = 1 ,20.1    ,21.1,20.1,19.1
XS GIS Cut Line= 2
     1846867.515      371236.702     1847568.036      371533.577
#Sta/Elev= 30
       0 1233.87    29.3 1220.31    68.3 1201.46   107.3 1180.43     117 1173.99
   126.8 1166.78   165.8 1135.98   175.6 1129.32   185.3  1124.1   195.1 1122.04
   214.6 1120.95   273.1 1116.19   321.9  1115.7   429.2 1117.76   438.9 1117.24
   458.4 1112.82   468.2 1111.77     478  1112.6   487.7 1115.63   497.5 1119.68
   507.2 1122.43   526.7 1124.44   536.5  1131.2   546.2    1143     556 1152.64
   565.8 1159.43   604.8 1182.68   682.8 1230.56   721.8 1252.88   760.8 1273.51
#Mann= 3 , 0 , 0
       0     .06       0   458.4    .045       0     478      .1       0
#XS Ineff= 2 , 0
       0     385    1130               0
Permanent Ineff=
       F       F
Bank Sta=458.4,478
XS Rating Curve= 0 ,0
Exp/Cntr=0.3,0.1

Chan Stop Cuts=-1
Use User Specified Reach Order=0
Composite Channel Slope=5